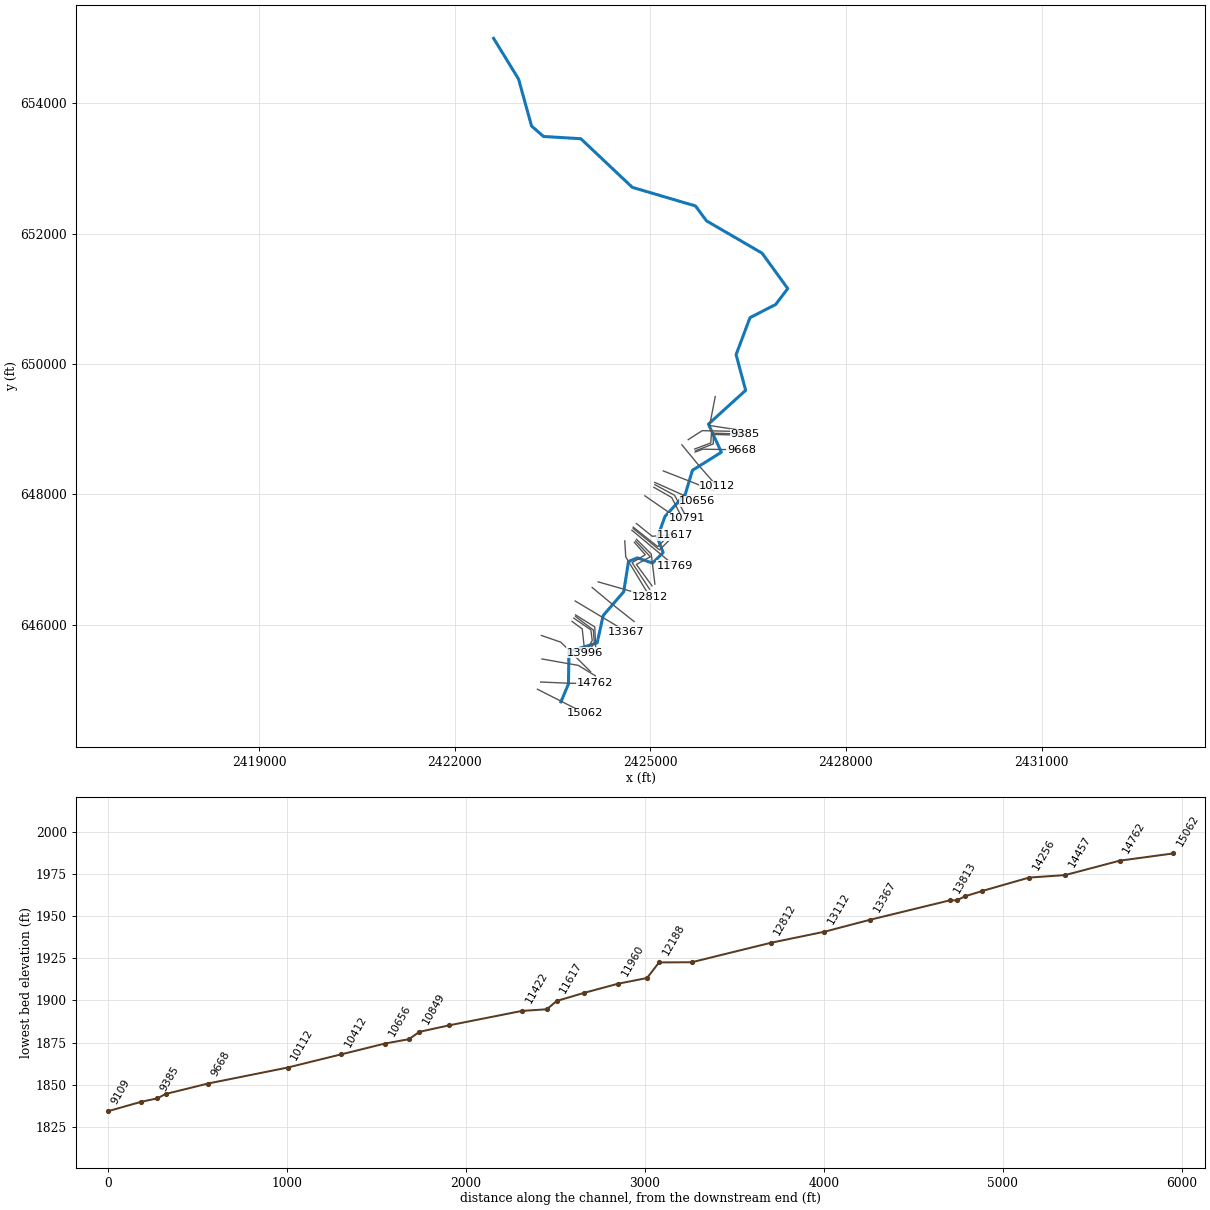
--- MILLCK.prj (project) ---

Proj Title=MILLCK
Current Plan=p01
Default Exp/Contr=0,0
English Units
Geom File=g01
Flow File=f01
Plan File=p01
BEGIN DESCRIPTION:
Stream Name: Mill Creek
Flood Zone: Approximate
Pendleton County, West Virginia
HEC-RAS Version: 5.0.7
Hydrology Method:
Regression equation
END DESCRIPTION:
DSS File=dss
DSS Export Rating Curves= 0
DSS Export Rating Curve Sorted= 0
DSS Export Volume Flow Curves= 0
DXF OffsetX= 0
DXF OffsetY= 0
DXF ScaleX= 0
DXF ScaleY= 0

--- MILLCK.p01 (plan) ---

Plan Title=Floodplain
Program Version=5.07
Short Identifier=Floodplain
Geom File=g01
Flow File=f01
Subcritical Flow
K Sum by GR= 0
Std Step Tol= 0.01
Critical Tol= 0.01
Num of Std Step Trials= 20
Max Error Tol= 0.3
Flow Tol Ratio= 0.001
Split Flow NTrial= 30
Split Flow Tol= 0.02
Split Flow Ratio= 0.02
Log Output Level= 0
Friction Slope Method= 1
Unsteady Friction Slope Method= 2
Unsteady Bridges Friction Slope Method= 1
Parabolic Critical Depth
Global Vel Dist= 0 , 0 , 0
Global Log Level= 0
CheckData=True
Encroach Param=-1 ,0,0, 0
Computation Interval=0.1SEC
Output Interval=1MIN
Instantaneous Interval=Max Profile
Mapping Interval=1HOUR
Computation Time Step Use Courant=        0
Computation Time Step Use Time Series=    0
Computation Time Step Count To Double=0
Computation Time Step Max Doubling=0
Computation Time Step Max Halving=0
Computation Time Step Residence Courant=0
Run HTab= 0
Run UNet= 0
Run Sediment= 0
Run PostProcess= 0
Run WQNet= 0
Run RASMapper= 0
UNET Theta= 0
UNET Theta Warmup= 0
UNET ZTol= 0
UNET ZSATol= 0
UNET MxIter= 0
UNET Max Iter WO Improvement= 0
UNET MaxInSteps= 0
UNET DtIC= 0
UNET DtMin= 0
UNET MaxCRTS= 0
UNET WFStab= 0
UNET SFStab= 0
UNET WFX= 1
UNET SFX= 1
UNET 1D Methodology=Finite Difference
UNET DSS MLevel= 1
UNET Pardiso=0
UNET DZMax Abort= 0
UNET Use Existing IB Tables= 0
UNET Froude Reduction=False
UNET Froude Limit= 0
UNET Froude Power= 0
UNET D1 Cores= 0
UNET D2 Coriolis=0
UNET D2 Cores= 0
UNET D2 Theta= 1
UNET D2 Theta Warmup= 1
UNET D2 Z Tol= 0.01
UNET D2 Volume Tol= 0.01
UNET D2 Max Iterations= 20
UNET D2 Equation= 0
UNET D2 RampUpFraction=0.1
UNET D2 TimeSlices= 1
UNET D2 BCVolumeCheck=0
UNET D1D2 MaxIter= 0
UNET D1D2 ZTol=0.01
UNET D1D2 QTol=0.1
UNET D1D2 MinQTol=1
DSS File=dss
Write IC File= 0
Write IC File at Fixed DateTime=0
Write IC File at Sim End=0
Echo Input=False
Echo Parameters=False
Echo Output=False
Write Detailed= 0
HDF Write Warmup=0
HDF Write Time Slices=0
HDF Flush=0
HDF Face Node Velocities=0
HDF Compression= 1
HDF Chunk Size= 1
HDF Spatial Parts= 1
HDF Use Max Rows=0
HDF Fixed Rows= 1
Calibration Method= 0
Calibration Iterations= 20
Calibration Max Change=0.05
Calibration Tolerance=0.2
Calibration Maximum=1.5
Calibration Minimum=0.5
Calibration Optimization Method= 1
WQ AD Non Conservative
WQ ULTIMATE=-1
WQ Max Comp Step=1HOUR
WQ Output Interval=15MIN
WQ Output Selected Increments= 0
WQ Output face flow=0
WQ Output face velocity=0
WQ Output face area=0
WQ Output face dispersion=0
WQ Output cell volume=0
WQ Output cell surface area=0
WQ Output cell continuity=0
WQ Output cumulative cell continuity=0
WQ Output face conc=0
WQ Output face dconc_dx=0
WQ Output face courant=0
WQ Output face peclet=0
WQ Output face adv mass=0
WQ Output face disp mass=0
WQ Output cell mass=0
WQ Output cell source sink temp=0
WQ Output nsm pathways=0
WQ Output nsm derived pathways=0
WQ Output MaxMinRange=-1
WQ Daily Max Min Mean=-1
WQ Daily Range=0
WQ Daily Time=0
WQ Create Restart=0
WQ Fixed Restart=0
WQ System Summary=0
WQ Write To DSS=0
WQ Use Fixed Temperature=0
Sorting and Armoring Iterations= 10
XS Update Threshold= 0.02
Bed Roughness Predictor= 0
Hydraulics Update Threshold= 0.02
Energy Slope Method= 1
Volume Change Method= 1
Sediment Retention Method= 0
XS Weighting Method= 0
Number of US Weighted Cross Sections= 1
Number of DS Weighted Cross Sections= 1
Upstream XS Weight=0
Main XS Weight=1
Downstream XS Weight=0
Number of DS XS's Weighted with US Boundary= 1
Upstream Boundary Weight= 1
Weight of XSs Associated with US Boundary= 0
Number of US XS's Weighted with DS Boundary= 1
Downstream Boundary Weight= 0.5
Weight of XSs Associated with DS Boundary= 0.5
Percentile Method= 0
Sediment Output Level= 3
Mass or Volume Output= 0
Output Increment Type= 1
Profile and TS Output Increment= 1
XS Output Flag= 0
XS Output Increment= 10
Write Gradation File= 0
Read Gradation Hotstart= 0
Write HDF5 File= 1
Write Binary Output= 1
Write DSS Sediment File= 0
SV Curve= 0
Specific Gage Flag= 0

--- MILLCK.f01 (steady flow) ---

Flow Title=Flows
Program Version=5.07
Number of Profiles= 6
Profile Names=P100yr,P10yr,P25yr,P50yr,P500yr,P101yr
River Rch & RM=MILLCK,Main            ,15062
     464     218     308     384     679     565
River Rch & RM=MILLCK,Main            ,13367
     639     298     422     527     937     777
River Rch & RM=MILLCK,Main            ,12371
     814     379     537     671    1198     991
River Rch & RM=MILLCK,Main            ,11012
     961     446     633     792    1417    1170
River Rch & RM=MILLCK,Main            ,9294
    1244     575     817    1024    1838    1514
River Rch & RM=MILLCK,Main            ,5909
    1506     694     988    1239    2230    1833
River Rch & RM=MILLCK,Main            ,5459
    1962     901    1284    1613    2913    2388
Boundary for River Rch & Prof#=MILLCK,Main            , 1
Up Type= 0
Dn Type= 3
Dn Slope=0.01812
Boundary for River Rch & Prof#=MILLCK,Main            , 2
Up Type= 0
Dn Type= 3
Dn Slope=0.01812
Boundary for River Rch & Prof#=MILLCK,Main            , 3
Up Type= 0
Dn Type= 3
Dn Slope=0.01812
Boundary for River Rch & Prof#=MILLCK,Main            , 4
Up Type= 0
Dn Type= 3
Dn Slope=0.01812
Boundary for River Rch & Prof#=MILLCK,Main            , 5
Up Type= 0
Dn Type= 3
Dn Slope=0.01812
Boundary for River Rch & Prof#=MILLCK,Main            , 6
Up Type= 0
Dn Type= 3
Dn Slope=0.01812
DSS Import GetInterval= 0
DSS Import GetPeak= 0
DSS Import FillOption= 0

--- MILLCK.g01 (geometry) ---

Geom Title=Geometry
Program Version=5.07

River Reach=MILLCK          ,Main
Reach XY= 30
     2423630.037       644817.78     2423745.624      645091.328
     2423753.111       645590.92     2424185.416      645721.842
     2424277.695      646141.666     2424593.211      646507.725
     2424666.146      646970.936     2424802.741      647028.193
     2425035.031      646946.953     2425197.151      647108.014
      2425109.25      647341.454      2425226.23      647663.784
     2425536.815      648003.239     2425646.649      648370.974
     2426090.499      648648.578     2425891.912      649079.142
     2426462.824      649598.434     2426316.282      650145.659
     2426529.768      650713.679     2426922.473      650914.636
     2427108.106       651160.01     2426714.592      651702.994
     2425862.086      652198.979     2425693.107      652427.515
     2424725.249      652712.596     2423935.368      653458.913
     2423362.553      653493.413     2423179.375      653655.048
     2422980.953      654373.417     2422597.846      654999.273

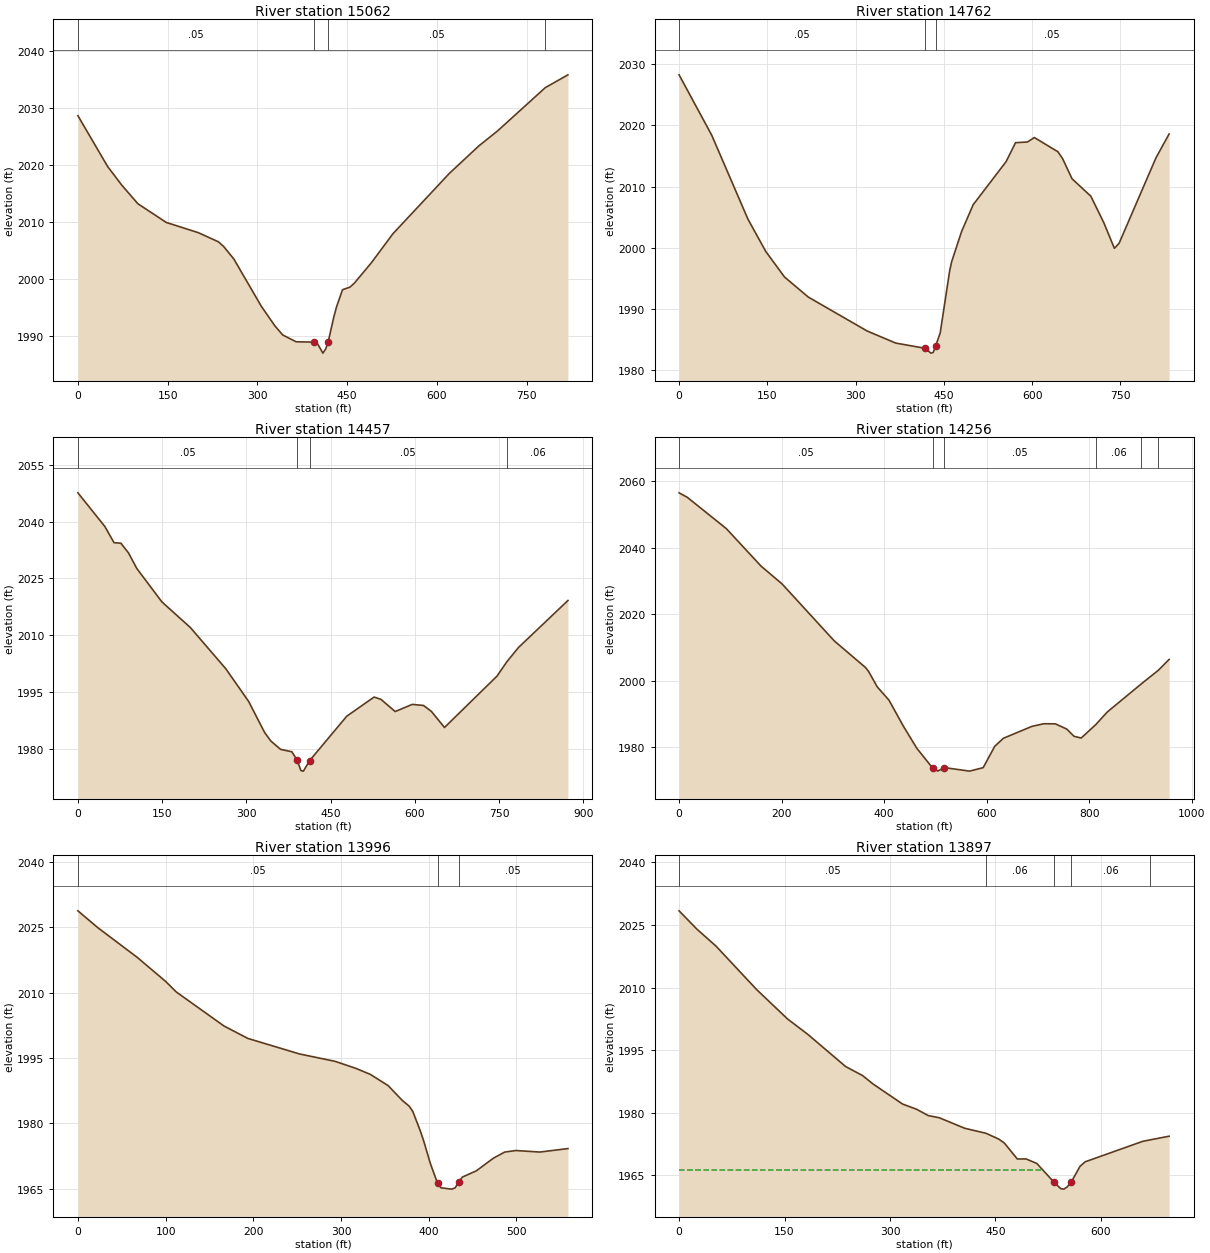
Type RM Length L Ch R = 1 ,15062   ,296,300,304.2
XS GIS Cut Line= 3
     2423269.475      645012.165     2423634.566      644826.696
     2423999.657      644641.226
#Sta/Elev= 30
       0 2028.61    49.5 2019.75    73.2 2016.48   100.1 2013.22   147.7 2009.94
   201.2 2008.15   234.7 2006.56   243.7 2005.72   260.7 2003.53   306.5 1995.28
   329.2 1991.85   342.4 1990.25   364.8 1989.06   394.6 1989.01   400.6 1988.69
   409.5 1987.08   414.2 1987.83   418.4  1989.1   427.6 1993.36   432.1 1995.12
   442.2 1998.17   454.6 1998.62   462.1 1999.33   490.5 2002.89   526.4 2007.95
   620.6  2018.5   669.9 2023.31   701.1 2025.92  781.192033.524     819 2035.76
#Mann= 4 ,-1 , 0
       0     .05       0   394.6    .045       0   418.4     .05       0
  781.19     .06       0
Bank Sta=394.6,418.4
XS Rating Curve= 0 ,0
Exp/Cntr=0.3,0.1

Type RM Length L Ch R = 1 ,14762   ,306.6,305.3,302.8
XS GIS Cut Line= 3
2423319.34580152645122.484809133     2423745.048      645103.821
     2424151.724      645099.894
#Sta/Elev= 30
       0 2028.26    55.5 2018.39     117 2004.68   147.5 1999.37   179.3 1995.21
   219.6 1991.94   319.7 1986.39   368.3 1984.42   418.61983.562   427.8 1982.78
   431.8 1982.89   435.8 1983.88   443.8 1986.09   459.8  1996.2   463.2 1997.71
   480.2 2002.67   499.8 2007.03   555.8 2014.08   571.8 2017.17   591.8 2017.28
   603.8 2018.01   643.8 2015.69   651.8 2014.56   667.8 2011.28   699.8 2008.42
   721.9 2004.08   739.8 1999.91   747.8 2000.73   810.6 2014.72   832.8 2018.59
#Mann= 3 ,-1 , 0
       0     .05       0   418.6    .045       0   435.8     .05       0
Bank Sta=418.6,435.8
XS Rating Curve= 0 ,0
Exp/Cntr=0.3,0.1

Type RM Length L Ch R = 1 ,14457   ,206.9,201,193.2
XS GIS Cut Line= 3
     2423339.438      645475.9632423895.72871019645377.481812939
     2424158.656      645217.979
#Sta/Elev= 30
       0 2047.57      48 2038.69    64.3 2034.43    76.5  2034.3    90.1 2031.73
   104.9 2027.63   149.6 2018.82   200.2 2012.08   263.3 2001.22     304  1992.6
   332.4 1984.43   343.3 1982.21   360.8 1979.98   381.1 1979.33   390.3  1977.1
   397.2 1974.36   401.5 1974.24   412.4 1976.98   478.6  1988.7   527.4 1993.76
   539.6 1993.15   564.9 1989.94   595.2 1991.82   615.3 1991.54   629.3 1989.99
   652.7 1985.74   746.3 1999.29  763.882003.091   784.5 2006.82   872.5  2019.2
#Mann= 4 ,-1 , 0
       0     .05       0   390.3    .045       0   412.4     .05       0
  763.88     .06       0
Bank Sta=390.3,412.4
XS Rating Curve= 0 ,0
Exp/Cntr=0.3,0.1

Type RM Length L Ch R = 1 ,14256   ,266.2,260.6,250.5
XS GIS Cut Line= 3
2423331.54790522645836.4575108082423628.62782298645733.817796608
2424084.38325937645282.034198478
#Sta/Elev= 30
       0 2056.58    16.1 2055.22    92.3 2045.78     160  2034.5   200.8 2029.17
   302.6 2012.02   363.9 2003.95   369.6 2002.83   386.6 1998.15   409.4 1994.17
   437.8 1986.26   463.7 1979.68   494.6 1973.73   504.6  1972.8   517.3 1973.85
   566.8 1972.78   593.3 1973.83   615.8 1980.25   632.7 1982.67   688.4 1986.26
   711.6 1987.05   734.1 1987.02   756.3 1985.45   770.4 1983.28   784.4 1982.74
  812.991986.794   835.5  1990.6  901.331998.996  935.052003.154     956 2006.42
#Mann= 6 ,-1 , 0
       0     .05       0   494.6    .045       0   517.3     .05       0
  812.99     .06       0  901.33     .05       0  935.05     .06       0
Bank Sta=494.6,517.3
XS Rating Curve= 0 ,0
Exp/Cntr=0.3,0.1

Type RM Length L Ch R = 1 ,13996   ,105.2,98.4,90.4
XS GIS Cut Line= 3
2423800.32911963646052.3967120722423956.69288526645937.851162832
2423996.69291833 645575.12359024
#Sta/Elev= 30
       0 2028.83    22.8 2024.94    67.5 2018.16   100.1  2012.6   112.1  2010.2
   166.6 2002.36   193.8 1999.51   252.7 1995.94   293.4 1994.24     317 1992.63
   333.6 1991.23   353.8 1988.66   369.9 1985.27   377.9 1983.92   381.9 1982.72
   390.5 1978.24   394.1 1976.09     402 1970.72   410.1 1966.25   414.1 1965.18
   426.2 1964.88   430.2 1965.18     434 1966.43   438.3 1967.64   454.4 1969.09
   473.8 1971.99   486.6 1973.39   499.2 1973.75   526.8  1973.4   558.8  1974.2
#Mann= 3 ,-1 , 0
       0     .05       0   410.1    .045       0     434     .05       0
Bank Sta=410.1,434
XS Rating Curve= 0 ,0
Exp/Cntr(USF)=0,0
Exp/Cntr=0.5,0.3

Type RM Length L Ch R = 1 ,13897   ,45.2,44.8,46.5
XS GIS Cut Line= 4
2423827.59969446 646102.771203692424089.53516006645922.519508182
 2424109.9315038645760.6981544862424004.34499041 645572.37377605
#Sta/Elev= 30
       0 2028.39    25.2 2024.02    52.4 2019.95   110.6 2009.46   154.3 2002.46
   183.4 1998.73   236.9 1991.05   261.2 1988.87   275.7 1986.89     318 1982.05
   337.7 1980.82   354.5 1979.29     370 1978.78   406.3 1976.25  436.481975.056
   454.7 1973.66   462.7  1972.7   481.1 1968.89   493.5  1968.9   508.8 1967.82
   533.6 1963.26   542.8 1961.79   547.3 1961.66   551.9 1962.17   557.81963.357
   570.3 1967.13   577.6 1968.21   659.3 1973.11  670.531973.489     697 1974.35
#Mann= 5 ,-1 , 0
       0     .05       0  436.48     .06       0   533.6    .045       0
   557.8     .06       0  670.53     .05       0
#XS Ineff= 2 , 0
          517.45  1966.3  569.92            1967
Permanent Ineff=
       F       F
Bank Sta=533.6,557.8
XS Rating Curve= 0 ,0
Exp/Cntr=0.5,0.3

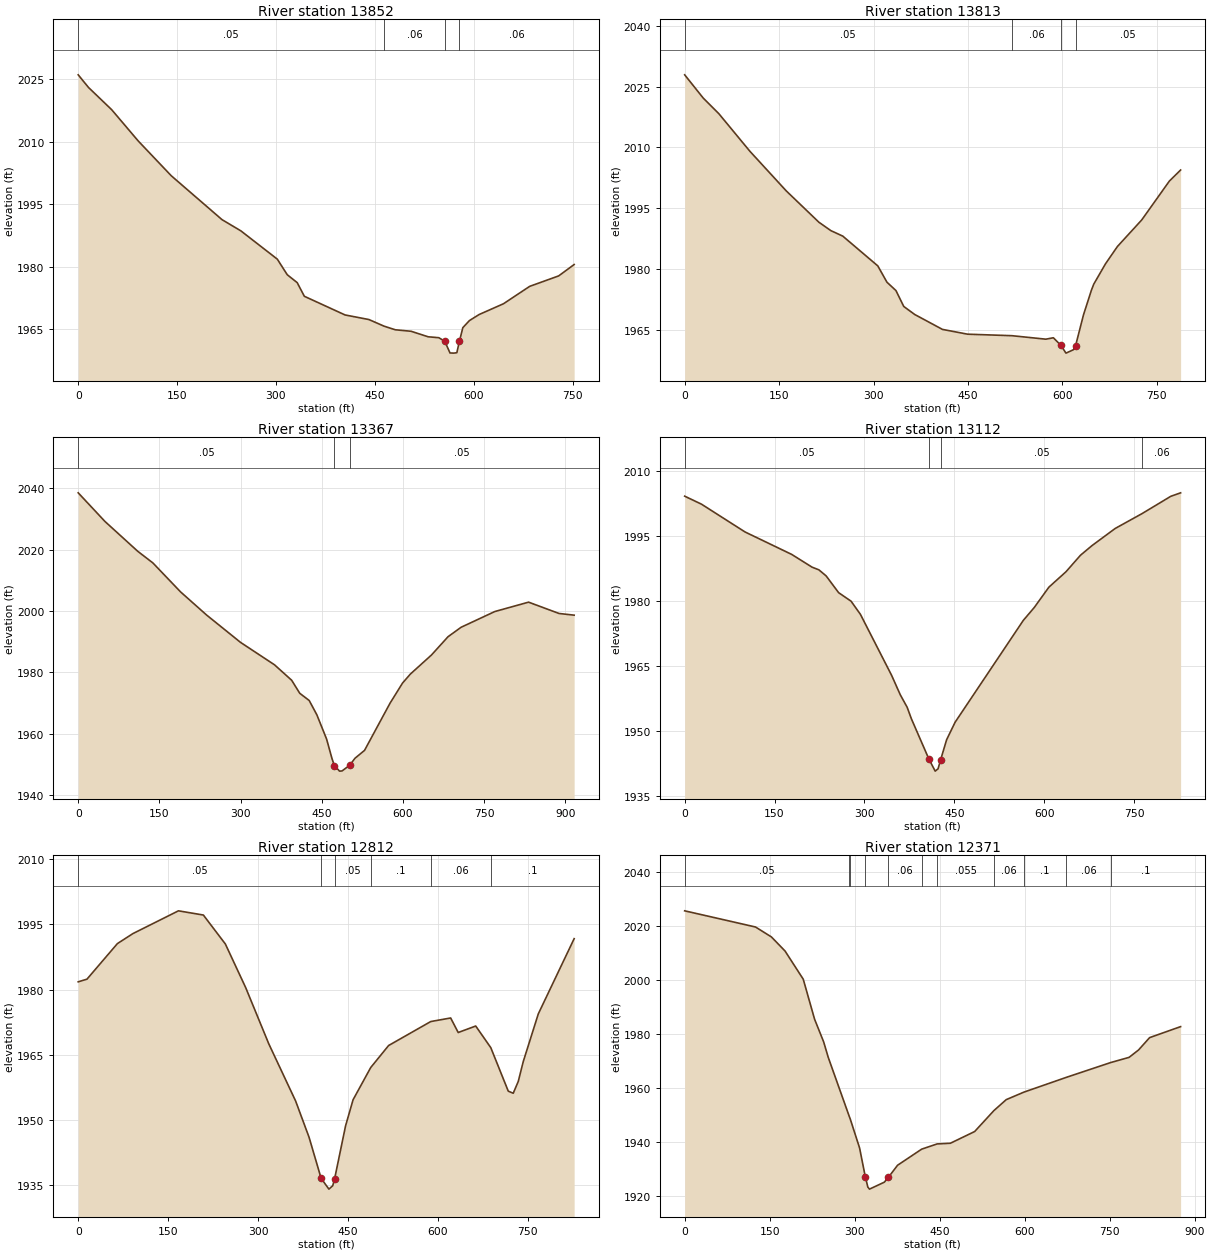
Type RM Length L Ch R = 1 ,13852   ,32.7,39.4,43.6
XS GIS Cut Line= 4
2423854.36409226646128.3180984082424127.35786249645920.499304492
 2424141.3720852645733.0776602752424035.51862392645538.595094247
#Sta/Elev= 30
       0 2026.09    15.6 2023.06    50.8 2017.72      91 2010.23   141.2 2001.87
   218.2 1991.34   246.8 1988.65   302.1 1981.86   317.2 1978.12   332.3 1976.22
   343.1 1972.95   404.9 1968.47   441.1 1967.37  463.971965.786   481.1 1964.91
   505.2 1964.55     531 1963.23   547.2 1963.01   556.3 1962.14   564.1 1959.35
  569.97 1959.31   574.5 1959.41   578.4 1962.14   583.6 1965.42   593.6 1967.12
   608.3 1968.57   645.3 1971.16     685 1975.33     729 1977.84   752.5 1980.57
#Mann= 4 ,-1 , 0
       0     .05       0  463.97     .06       0   556.3    .045       0
   578.4     .06       0
Bank Sta=556.3,578.4
XS Rating Curve= 0 ,0
Exp/Cntr=0.5,0.3

Type RM Length L Ch R = 1 ,13813   ,433.7,446.4,452.7
XS GIS Cut Line= 3
2423853.81337491646152.6899248732424148.95250036645968.341758086
 2424169.7688947645528.974985638
#Sta/Elev= 30
       0 2027.92    29.4  2022.2    54.2 2018.35   103.6 2009.07   161.4 1999.29
   213.3 1991.56   232.2  1989.5   251.1 1988.15   306.8  1980.8   321.3 1976.78
   335.6 1974.72     348  1970.8   365.5 1968.81   409.5 1965.14   449.5 1963.96
  519.77 1963.59   573.7 1962.73   585.7 1963.08   597.7 1961.19   605.7 1959.29
   617.7 1960.14   620.9 1961.09   633.5 1968.72   646.1 1974.81   649.8 1976.29
   668.4  1981.3   687.5  1985.6     726 1992.13   769.9 2001.71   787.8 2004.45
#Mann= 4 ,-1 , 0
       0     .05       0  519.77     .06       0   597.7    .045       0
   620.9     .05       0
Bank Sta=597.7,620.9
XS Rating Curve= 0 ,0
Exp/Cntr=0.3,0.1

Type RM Length L Ch R = 1 ,13367   ,255.8,254.1,251.3
XS GIS Cut Line= 2
2423848.33682617646365.847729116 2424634.6595659645895.689418533
#Sta/Elev= 30
       0 2038.49    49.4 2029.16     110 2019.43     138 2015.63   189.2 2006.18
   237.2 1998.65   299.8 1989.75   362.7 1982.42   394.3  1977.4   409.3 1973.14
   426.7  1970.8   440.9 1966.12   458.9 1958.21   468.9 1951.82   473.4 1949.53
   482.8 1947.77   487.5 1947.84   501.5 1949.68   511.4 1951.98   528.9 1954.52
     576 1969.89   599.3 1976.51   613.7 1979.42   652.7 1985.64   683.2 1991.58
   707.3 1994.66   769.6 1999.79     832 2002.85   888.3 1999.16   916.2 1998.61
#Mann= 3 ,-1 , 0
       0     .05       0   473.4    .045       0   501.5     .05       0
Bank Sta=473.4,501.5
XS Rating Curve= 0 ,0
Exp/Cntr(USF)=0,0
Exp/Cntr=0.3,0.1

Type RM Length L Ch R = 1 ,13112   ,294.3,300,303.4
XS GIS Cut Line= 3
2424109.20955572646572.844370478     2424431.026      646305.369
     2424751.639       646051.04
#Sta/Elev= 30
       0 2004.12    28.1 2002.27   100.8 1995.86   178.6 1990.69   212.7 1987.74
     224 1987.13   236.1 1985.73   256.9 1981.87   277.7  1979.9   293.3 1976.87
   345.3 1962.82   359.8 1958.33   371.3 1955.44   378.5 1952.74   407.7 1943.46
   418.1 1940.71   422.9 1941.25   427.21943.325   437.1 1947.93   451.3 1951.98
   565.2 1975.48   583.4 1978.44   607.9 1983.14   636.4 1986.69   660.6  1990.5
   679.9 1992.73   718.5 1996.67  763.452000.107   811.2 2004.08   827.7 2004.89
#Mann= 4 ,-1 , 0
       0     .05       0   407.7    .045       0   427.2     .05       0
  763.45     .06       0
Bank Sta=407.7,427.2
XS Rating Curve= 0 ,0
Exp/Cntr=0.3,0.1

Type RM Length L Ch R = 1 ,12812   ,446.7,441.3,416.9
XS GIS Cut Line= 3
2424201.95401142646658.878423595     2424604.174      646544.277
     2424996.048      646427.005
#Sta/Elev= 30
       0  1981.8    14.6 1982.41    65.4 1990.59    91.3 1992.89   167.2 1998.12
   208.8 1997.15   245.5 1990.49   279.5 1980.43   317.8 1967.58   362.7  1954.4
   385.1 1946.07   405.2 1936.64   418.2 1934.15   424.6 1934.94   427.8 1936.58
     446  1948.7   458.5 1954.69  487.931962.094   517.8 1967.16  588.09 1972.67
   621.3 1973.49   633.9 1970.15   663.1 1971.64  688.251966.667   717.4 1956.67
   725.7 1956.19   734.1 1958.91   742.4 1963.47   767.5 1974.43   827.3 1991.72
#Mann= 6 ,-1 , 0
       0     .05       0   405.2    .045       0   427.8     .05       0
  487.93      .1       0  588.09     .06       0  688.25      .1       0
Bank Sta=405.2,427.8
XS Rating Curve= 0 ,0
Exp/Cntr=0.3,0.1

Type RM Length L Ch R = 1 ,12371   ,195.6,182.9,161.3
XS GIS Cut Line= 3
2424609.36243662647287.6830068442424624.23074236647041.507804739
2424949.84418278646504.083905802
#Sta/Elev= 30
       0  2025.7     125 2019.71   153.1 2016.02   177.1 2010.81   209.2 2000.38
   229.2 1985.57   245.2 1977.18   253.3 1971.44  290.74 1949.37  292.241948.536
   308.6 1937.89   318.61927.323   323.2  1923.4   326.1 1922.65   352.3 1925.23
   359.5 1927.04   375.6 1931.49  418.141937.454  445.411939.387   468.8 1939.64
   511.6 1943.97  545.551951.721   567.3 1955.78  598.591958.574  672.951964.008
  751.761969.529   784.1 1971.44   800.8 1974.18   820.3 1978.75     875 1982.82
#Mann= 11 ,-1 , 0
       0     .05       0  290.74      .1       0  292.24     .06       0
   318.6    .045       0   359.5     .06       0  418.14      .1       0
  445.41    .055       0  545.55     .06       0  598.59      .1       0
  672.95     .06       0  751.76      .1       0
Bank Sta=318.6,359.5
XS Rating Curve= 0 ,0
Exp/Cntr=0.5,0.3

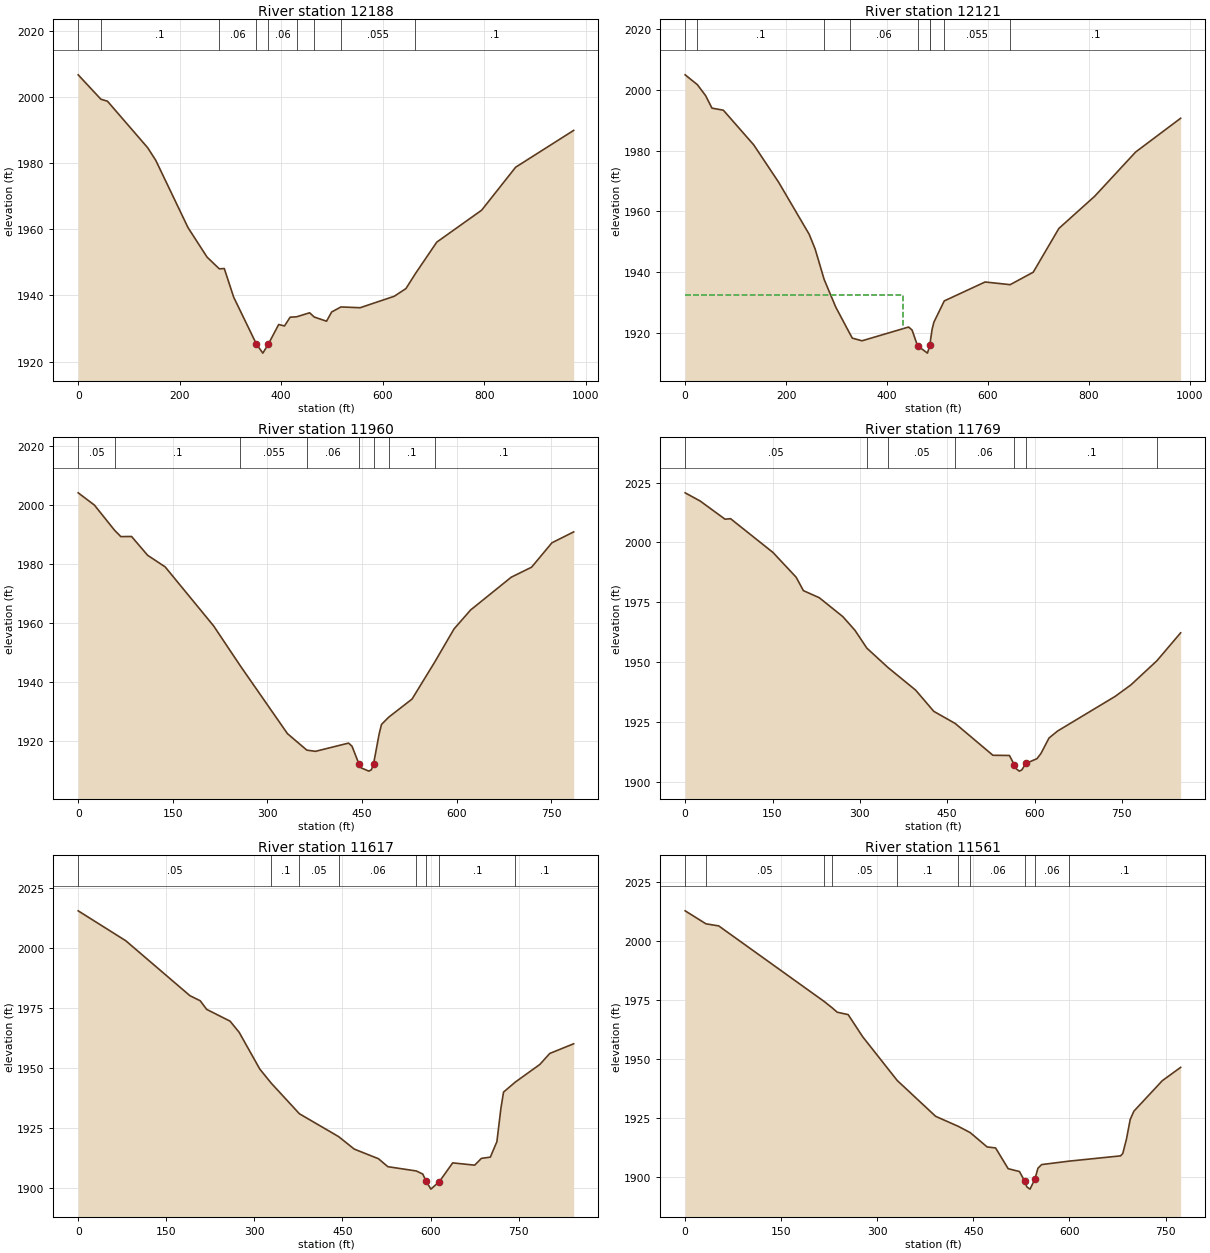
Type RM Length L Ch R = 1 ,12188   ,66,67.1,65.9
XS GIS Cut Line= 4
2424756.13329197647265.7252264962424923.85621042647075.058757352
2424721.46455704646953.7651258872424989.04934779646547.423054836
#Sta/Elev= 30
       0 2006.63   44.78 1999.25    57.7 1998.66     137 1984.59   152.9 1980.79
   216.4 1960.47   253.9 1951.56  278.011948.009   287.9 1948.09   306.5 1939.41
   351.1 1925.31  363.85 1922.53   374.4 1925.17   395.1 1931.18   406.5 1930.74
   417.7 1933.39  430.491933.514   456.1 1934.72  465.211933.435   489.4 1932.18
   499.5 1934.97  517.791936.487   555.6 1936.25   622.8 1939.71   645.9 1942.04
  664.581946.569   706.6 1956.07   795.1 1965.73   862.1 1978.72   976.4 1989.84
#Mann= 9 ,-1 , 0
       0     .05       0   44.78      .1       0  278.01     .06       0
   351.1    .045       0   374.4     .06       0  430.49    .055       0
  465.21     .06       0  517.79    .055       0  664.58      .1       0
#XS Ineff= 2 , 0
           351.1  1923.4  377.41         1925.79
Permanent Ineff=
       F       F
Bank Sta=351.1,374.4
XS Rating Curve= 0 ,0
Exp/Cntr=0.5,0.3

Type RM Length L Ch R = 1 ,12121   ,149.2,161,177.6
XS GIS Cut Line= 4
2424774.98865757647286.2053083542425001.07975905647044.156319585
2424787.24965943646926.0641801782425027.47479523646598.322085625
#Sta/Elev= 30
       0 2004.95   24.33 2001.69    40.7 1998.06    53.1 1993.98    75.7  1993.3
   135.9 1981.88   185.2 1969.59   245.8 1952.42   257.5 1947.62  275.521937.511
   298.5 1928.43   325.91919.851   331.2 1918.23   350.4 1917.35   442.8 1921.89
   449.7 1920.88   460.4 1915.74   480.1 1913.29   484.7 1915.81  485.191916.434
   489.2 1921.01   492.8 1923.45  513.441930.488   594.3 1936.72  643.991935.838
   689.7 1939.94   740.5 1954.35   811.5 1964.96   892.6 1979.52   981.8 1990.65
#Mann= 9 ,-1 , 0
       0     .05       0   24.33      .1       0  275.52    .055       0
   325.9     .06       0   460.4    .045       0   484.7     .06       0
  485.19      .1       0  513.44    .055       0  643.99      .1       0
#XS Ineff= 2 , 0
          431.21 1932.34
Permanent Ineff=
       F       F
Bank Sta=460.4,484.7
XS Rating Curve= 0 ,0
Exp/Cntr=0.5,0.3

Type RM Length L Ch R = 1 ,11960   ,178.4,191.1,196.1
XS GIS Cut Line= 3
2424788.52682877 647312.282105472425015.68782507647085.466898155
2425071.45655789646624.680380789
#Sta/Elev= 30
       0 2004.29    25.7 2000.14    57.61991.618    67.6 1989.45    84.6 1989.49
     110 1983.13   137.8 1979.19   214.7 1959.16  257.13 1945.58   331.7 1922.64
  362.341917.071     376 1916.66   428.4 1919.45   433.9 1918.41   444.7 1912.51
   448.5 1911.05   460.6 1909.95   464.6 1910.41     4681912.317     477 1922.62
   480.7 1925.79  492.07 1928.23   529.1 1934.39     5651946.918   595.6 1958.15
   621.8 1964.56   686.2 1975.68   718.5 1979.08   750.7 1987.34   785.2 1991.05
#Mann= 8 ,-1 , 0
       0     .05       0    57.6      .1       0  257.13    .055       0
  362.34     .06       0   444.7    .045       0     468      .1       0
  492.07      .1       0     565      .1       0
Bank Sta=444.7,468
XS Rating Curve= 0 ,0
Exp/Cntr=0.3,0.1

Type RM Length L Ch R = 1 ,11769   ,141.4,152.4,172.3
XS GIS Cut Line= 2
2424718.80532233647451.3638851412425372.25392339646906.407704484
#Sta/Elev= 30
       0  2020.7    25.9 2017.26    68.5 2009.69      78  2009.9   150.8 1995.81
   190.6 1985.46   203.1 1979.85   230.3 1976.91   270.8    1969   291.6  1963.3
  312.031955.845  348.331947.747   395.8 1938.32     427 1929.45  463.741924.392
   528.5 1911.11   556.9 1911.03   565.5    1907   569.1 1905.35     574 1904.49
   578.1    1905   585.3 1907.72   604.1 1909.68   610.9 1911.81   624.9 1918.32
   639.3 1921.19   738.7 1935.74   765.6 1940.52  809.951950.532   850.9 1962.24
#Mann= 7 ,-1 , 0
       0     .05       0  312.03      .1       0  348.33     .05       0
  463.74     .06       0   565.5    .045       0   585.3      .1       0
  809.95      .1       0
Bank Sta=565.5,585.3
XS Rating Curve= 0 ,0
Exp/Cntr(USF)=0,0
Exp/Cntr=0.5,0.3

Type RM Length L Ch R = 1 ,11617   ,55.7,55.6,57.7
XS GIS Cut Line= 3
     2424738.154      647478.0382425141.53837106647149.858672644
2425371.69500556647377.328043898
#Sta/Elev= 30
       0 2015.38      81 2002.95   190.3  1980.1   207.8    1978   218.8 1974.41
   258.6 1969.53   274.1 1964.88   309.2 1949.61  328.761943.727  376.63 1931.04
  443.351921.548     470 1916.35   511.3 1912.34   527.2 1909.04  575.761907.255
   586.7 1905.97   592.3 1903.04   600.5 1899.71   614.9 1902.83   637.6 1910.62
   675.1 1909.67   686.5 1912.49   701.7 1913.01   712.9 1919.46   719.6 1933.09
   724.2 1940.04  744.211944.201     786 1951.53   802.9  1956.1   843.6 1960.13
#Mann= 8 ,-1 , 0
       0     .05       0  328.76      .1       0  376.63     .05       0
  443.35     .06       0  575.76      .1       0   592.3    .045       0
   614.9      .1       0  744.21      .1       0
#XS Ineff= 2 , 0
             582  1906.2  625.79          1906.2
Permanent Ineff=
       F       F
Bank Sta=592.3,614.9
XS Rating Curve= 0 ,0
Exp/Cntr=0.5,0.3

Type RM Length L Ch R = 1 ,11561   ,145.3,138.6,132.1
XS GIS Cut Line= 3
     2424737.773      647499.5062425115.26461107647199.161167511
2425317.42502949647408.761277496
#Sta/Elev= 30
       0 2012.73   32.52 2007.22    52.4 2006.34  217.221974.286  229.531971.622
   237.4 1969.77   254.5 1968.75   277.2 1959.36   331.11940.832   391.1 1925.64
  426.541921.385  444.981918.758   471.5 1912.67   484.7 1912.24   504.3 1903.46
     522 1902.24   529.9 1898.28   533.5 1895.74   538.4 1894.79     5461899.006
   550.8 1903.64   556.6 1905.19  599.381906.653   679.9 1908.89   683.3 1909.93
   689.1  1916.1   694.8 1924.25   700.6 1927.82   744.9 1940.73   773.6 1946.39
#Mann= 10 ,-1 , 0
       0      .1       0   32.52     .05       0  217.22      .1       0
  229.53     .05       0   331.1      .1       0  426.54     .05       0
  444.98     .06       0   529.9    .045       0     546     .06       0
  599.38      .1       0
Bank Sta=529.9,546
XS Rating Curve= 0 ,0
Exp/Cntr=0.5,0.3

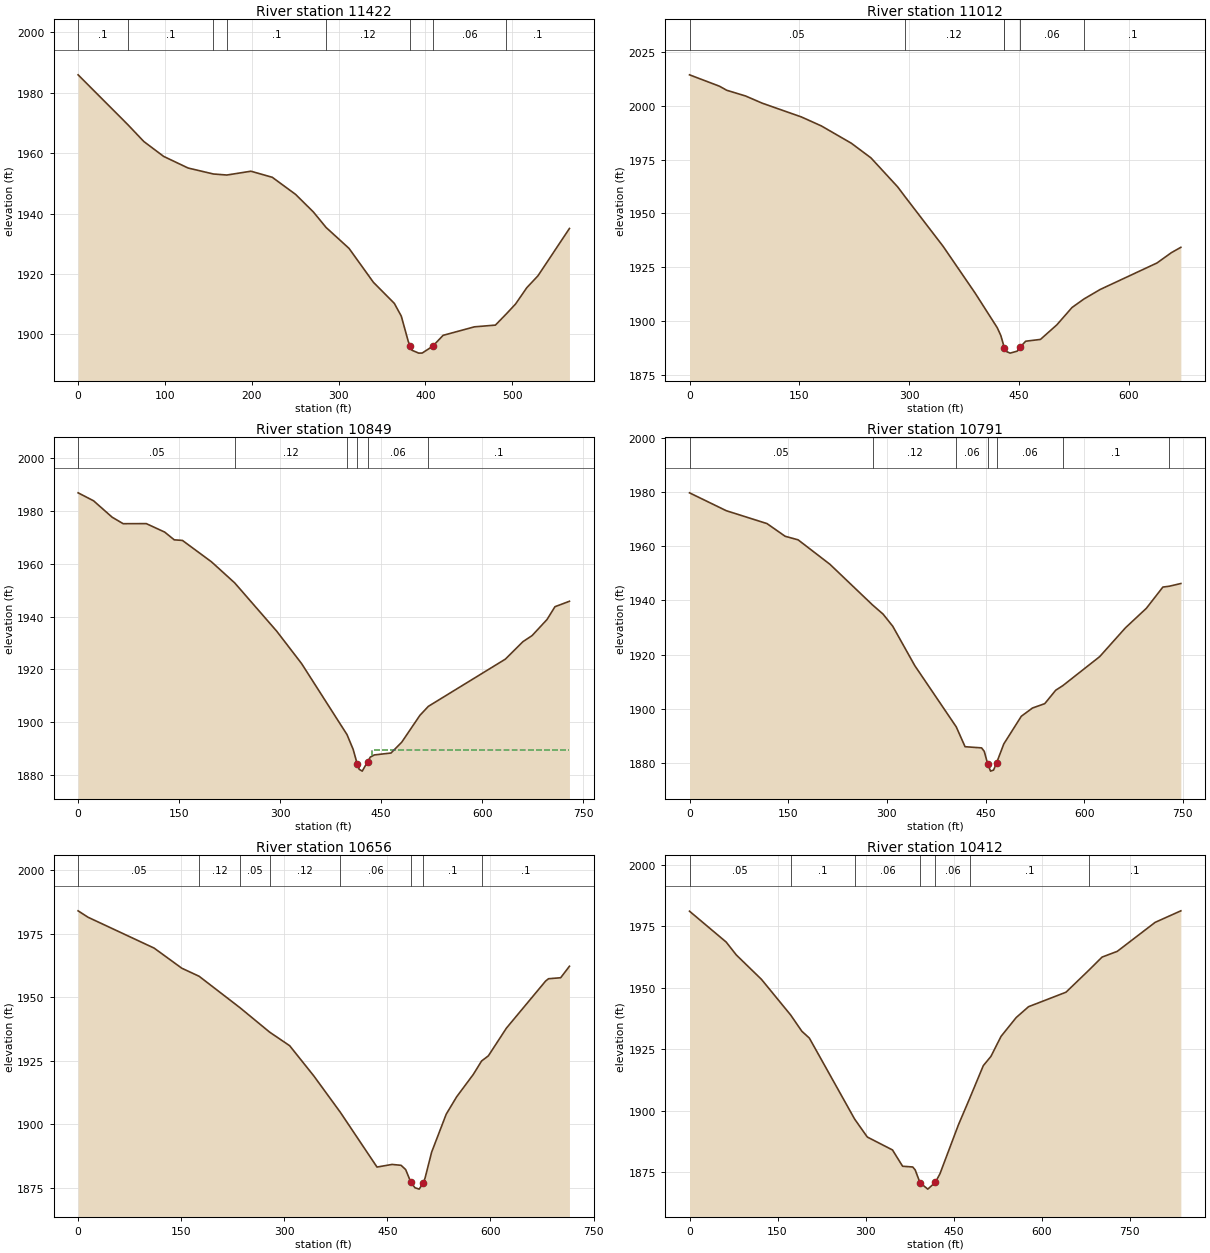
Type RM Length L Ch R = 1 ,11422   ,416.6,409.9,399.6
XS GIS Cut Line= 3
2424787.69781751647554.3649404772425030.61034091647358.699735662
  2425283.703842647381.397707657
#Sta/Elev= 30
       0  1985.9   57.091969.473    75.7 1963.84    98.5 1958.92   126.7 1955.07
  155.861953.091  171.361952.751   199.1 1954.01   223.7    1952   250.5 1946.35
     271 1940.54  285.631935.413   312.1 1928.48   340.2 1917.25   364.3 1910.28
   372.3 1906.07   380.3 1897.73   382.4  1896.2   384.3 1894.82   392.4 1893.83
   396.4 1893.86   408.4 1896.09   420.5 1899.72   456.6 1902.53   480.7  1903.1
  493.351906.826   503.9 1910.07   516.9 1915.49   529.7  1919.4     566 1935.07
#Mann= 8 ,-1 , 0
       0      .1       0   57.09      .1       0  155.86     .05       0
  171.36      .1       0  285.63     .12       0   382.4    .045       0
   408.4     .06       0  493.35      .1       0
Bank Sta=382.4,408.4
XS Rating Curve= 0 ,0
Exp/Cntr=0.3,0.1

Type RM Length L Ch R = 1 ,11012   ,167,163.4,159.4
XS GIS Cut Line= 3
2424917.01147573647979.678124642     2425277.375      647730.765
2425469.58708372647599.129056142
#Sta/Elev= 30
       0 2014.26      41 2008.97    50.7 2007.12    76.6 2004.44    99.3 2001.11
   152.8 1994.73   180.1 1990.56   220.9 1982.56   247.7 1975.77   284.1 1962.36
  293.981957.905   346.3 1934.74     390 1913.07   420.2 1897.02   425.1 1893.38
  428.841888.981   429.9 1887.75   433.1 1885.92   437.8 1885.23   447.5 1886.15
   451.9 1888.12     459 1890.75   479.2 1891.59   501.5 1898.32   522.3 1906.38
  538.611910.331   560.8 1914.75   638.4 1927.04   657.8 1931.77   670.9 1934.29
#Mann= 6 ,-1 , 0
       0     .05       0  293.98     .12       0  428.84     .06       0
   429.9    .045       0   451.9     .06       0  538.61      .1       0
Bank Sta=429.9,451.9
XS Rating Curve= 0 ,0
Exp/Cntr=0.5,0.3

Type RM Length L Ch R = 1 ,10849   ,57.9,58,58.1
XS GIS Cut Line= 3
     2425054.914      648110.4032425328.19374192647953.847302461
2425518.38243946647585.662061505
#Sta/Elev= 30
       0  1986.9    22.9 1983.89    50.5 1977.67    66.9  1975.2   101.2 1975.23
   128.5 1972.02   142.7 1969.09   154.9 1968.86     198 1960.75  232.521952.749
   294.8 1934.47   331.8 1922.17   399.2 1895.26   408.3 1889.68   414.21884.297
   417.3  1882.1   421.8 1881.42   429.91885.015   433.8 1886.75   439.8 1887.56
   464.5 1888.28   480.4 1892.38   507.4 1902.56  519.991905.981   634.3 1923.87
   660.4  1930.5   673.9 1932.78   696.1 1938.88   707.9 1943.74   729.4  1945.8
#Mann= 6 ,-1 , 0
       0     .05       0  232.52     .12       0   399.2     .06       0
   414.2    .045       0   429.9     .06       0  519.99      .1       0
#XS Ineff= 2 , 0
          409.16  1886.7  436.68          1889.5
Permanent Ineff=
       F       F
Bank Sta=414.2,429.9
XS Rating Curve= 0 ,0
Exp/Cntr=0.5,0.3

Type RM Length L Ch R = 1 ,10791   ,130.2,134.6,140.3
XS GIS Cut Line= 3
2425070.81879836 648150.637506032425372.17257959647988.033376025
2425565.84023782647632.906859865
#Sta/Elev= 30
       0 1979.69    55.9  1973.1   117.8 1968.35   145.4 1963.67   165.1 1962.36
   213.5 1953.34  278.221938.361   294.3 1934.97     309 1930.49   342.4 1916.01
  405.491893.416   418.9  1886.1     444 1885.67   448.1 1884.37   453.1 1879.91
   457.6  1877.1   462.2 1877.49   466.7 1880.08   477.8 1887.14   504.4 1897.33
   521.4 1900.37     540 1901.97   556.7 1906.93  567.471908.608   623.5  1919.3
   662.7 1929.93   694.5 1937.13   719.6 1944.95  729.461945.264   746.9 1946.26
#Mann= 7 ,-1 , 0
       0     .05       0  278.22     .12       0  405.49     .06       0
   453.1    .045       0   466.7     .06       0  567.47      .1       0
  729.46      .1       0
Bank Sta=453.1,466.7
XS Rating Curve= 0 ,0
Exp/Cntr=0.5,0.3

Type RM Length L Ch R = 1 ,10656   ,244.2,244,243
XS GIS Cut Line= 2
2425069.60710106648185.0741260152425722.46814917647893.799494906
#Sta/Elev= 30
       0 1984.07    14.4 1981.55   110.7 1969.38   150.9 1961.47   176.11958.302
   235.31945.972  278.841936.279   307.8 1930.97   342.9 1919.09  381.581904.738
   434.9 1883.19   456.8 1884.22   469.9 1883.88   476.6  1882.2   484.1 1877.23
   490.1 1875.05   496.2  1874.5   502.3 1876.91     505 1879.04   514.4 1889.07
   535.6 1904.01   550.7 1910.82     575 1919.66  587.071924.948   596.9 1926.97
   623.2 1937.89   680.2 1956.42   684.5 1957.34   702.1 1957.72   714.9 1962.25
#Mann= 8 ,-1 , 0
       0     .05       0   176.1     .12       0   235.3     .05       0
  278.84     .12       0  381.58     .06       0   484.1    .045       0
   502.3      .1       0  587.07      .1       0
Bank Sta=484.1,502.3
XS Rating Curve= 0 ,0
Exp/Cntr=0.3,0.1

Type RM Length L Ch R = 1 ,10412   ,305.1,300,294.3
XS GIS Cut Line= 3
     2425200.538      648361.132     2425578.425      648213.804
     2425979.498      648054.754
#Sta/Elev= 30
       0 1981.07    62.5 1968.52    79.6 1963.32   122.6 1953.36  172.31 1938.88
   191.3  1932.3   204.2 1929.48  281.371896.551   302.9 1889.28   345.8 1884.03
     363 1877.41   380.3 1877.11   384.5  1875.9   392.6 1870.72   405.9 1868.11
   418.8 1870.86   426.6 1874.33     458 1894.19   477.11904.893   500.5  1918.3
   513.5 1922.07   530.7 1930.19   556.5 1937.84   577.5 1942.25   641.4 1948.15
   680.51957.132   702.8 1962.42   728.7 1964.75   793.2 1976.53     837 1981.22
#Mann= 7 ,-1 , 0
       0     .05       0  172.31      .1       0  281.37     .06       0
   392.6    .045       0   418.8     .06       0   477.1      .1       0
   680.5      .1       0
Bank Sta=392.6,418.8
XS Rating Curve= 0 ,0
Exp/Cntr=0.3,0.1

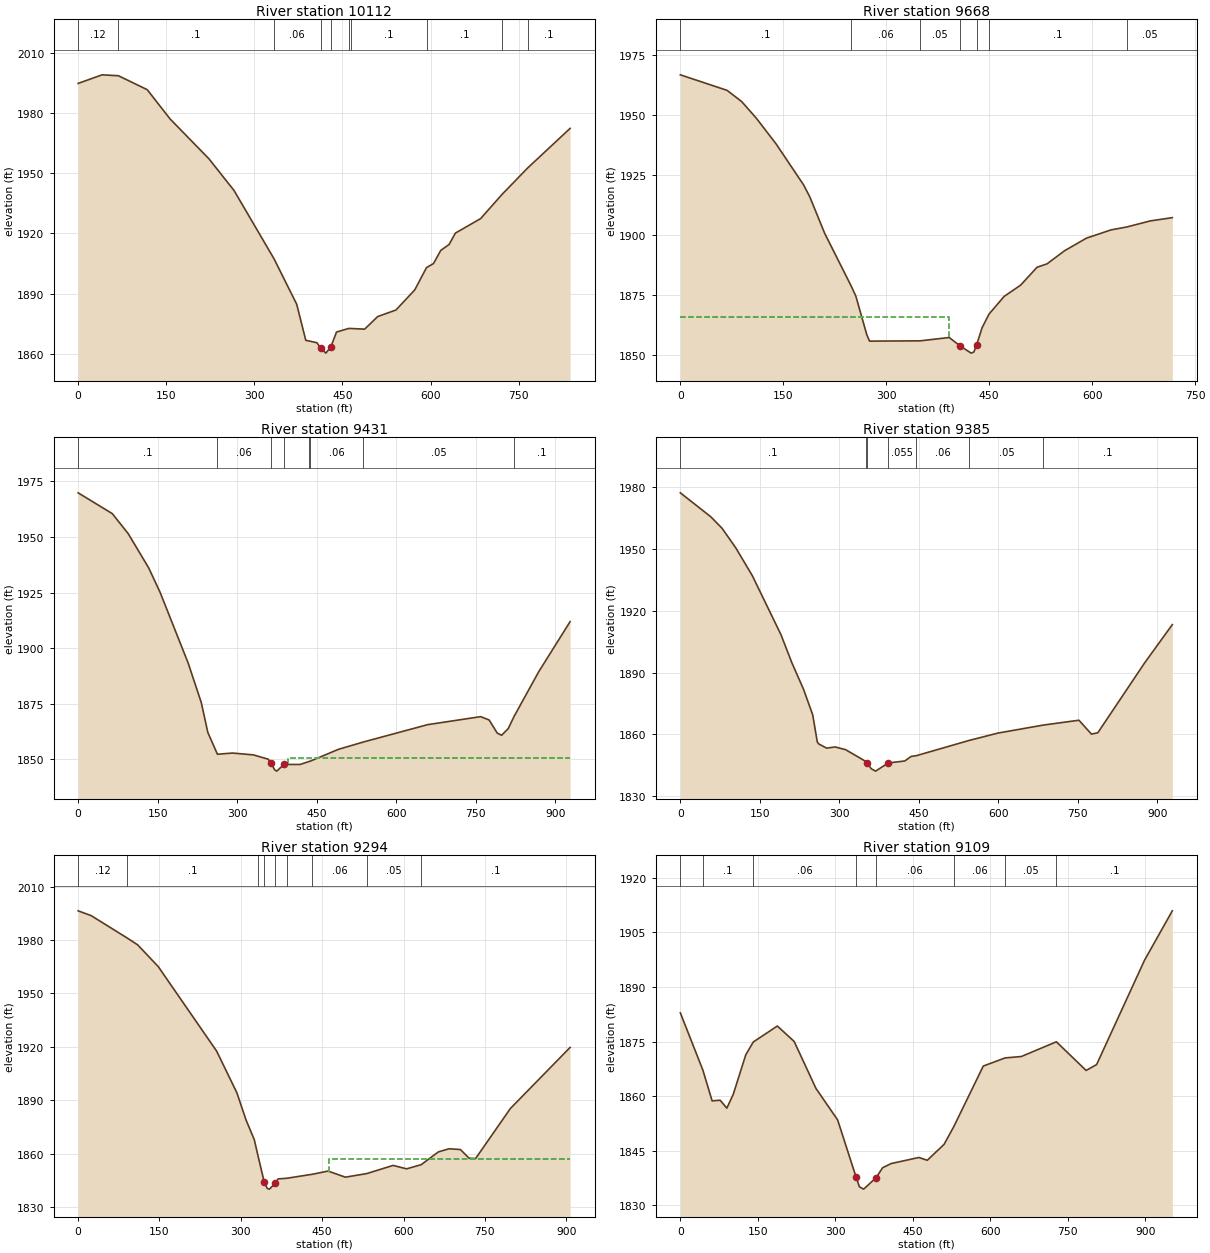
Type RM Length L Ch R = 1 ,10112   ,427.8,444.1,449.6
XS GIS Cut Line= 3
2425484.80014014648762.459825615     2425751.975      648437.086
     2426027.015      648124.239
#Sta/Elev= 30
       0 1994.85    40.9 1999.13   68.57 1998.67   117.6 1991.73   156.4 1977.17
   222.8  1957.2   265.4 1941.44  333.371907.427   372.1 1884.69   387.6 1866.68
   406.5 1865.48   412.8  1862.9   421.7 1860.28   430.2 1863.35   439.9 1870.79
  460.641872.595  464.511872.569   487.8 1872.25     510 1878.52   541.1 1881.79
   573.1 1891.82  593.171902.963     605 1904.97   617.3 1911.49   631.6  1914.5
   642.3 1920.16   685.3 1927.41  721.821939.499  765.081952.574   837.6 1972.41
#Mann= 10 ,-1 , 0
       0     .12       0   68.57      .1       0  333.37     .06       0
   412.8    .045       0   430.2     .06       0  460.64    .055       0
  464.51      .1       0  593.17      .1       0  721.82      .1       0
  765.08      .1       0
Bank Sta=412.8,430.2
XS Rating Curve= 0 ,0
Exp/Cntr=0.3,0.1

Type RM Length L Ch R = 1 ,9668    ,212.4,237.5,249.9
XS GIS Cut Line= 3
2425687.11149892 648650.639951122425805.58404355 648695.02446329
2426395.76787947648685.334051238
#Sta/Elev= 30
       0 1966.81      68 1960.35    89.3 1955.68   110.7 1948.74   139.7 1937.94
   179.7 1920.88   188.6 1915.96   210.4  1900.7  249.051878.711   255.7 1874.58
   271.7 1858.46   275.7 1855.83  349.411855.949   391.7 1857.34   407.2 1853.91
   423.7 1850.83   427.7 1851.31   431.81854.383   439.7 1861.46  449.771867.103
   471.7 1874.45   495.7 1879.14   519.7 1886.61   534.3 1888.04   559.7 1893.47
   591.7 1898.75   627.6 1902.19  650.49  1903.4   684.8 1905.94   716.8 1907.29
#Mann= 7 ,-1 , 0
       0      .1       0  249.05     .06       0  349.41     .05       0
   407.2    .045       0   431.8     .05       0  449.77      .1       0
  650.49     .05       0
#XS Ineff= 2 , 0
          391.22 1865.97
Permanent Ineff=
       F       F
Bank Sta=407.2,431.8
XS Rating Curve= 0 ,0
Exp/Cntr=0.5,0.3

Type RM Length L Ch R = 1 ,9431    ,44.4,45.5,55.2
XS GIS Cut Line= 4
2425694.58889893   648670.8882962425966.48693418648775.487109934
2425964.89274366648921.3396968112426455.39040666648907.810419199
#Sta/Elev= 30
       0 1969.86    64.5 1960.49    94.5 1951.47     133 1936.12   154.5 1925.14
   207.5 1893.29   232.3 1875.46   244.6 1862.05  262.741852.223   291.3 1852.77
   330.7 1851.93   358.7 1849.99   363.8 1848.25   370.7 1845.21   374.7 1844.63
     388 1847.64   418.7 1847.63  435.871848.998  437.41 1849.08   491.1 1854.45
  537.621857.705   659.1 1865.54   759.2 1869.14   775.2 1867.64   790.5 1861.75
   798.7 1860.75   811.2 1863.76  822.321869.278   868.6 1889.31   927.9 1911.89
#Mann= 8 ,-1 , 0
       0      .1       0  262.74     .06       0   363.8    .045       0
     388     .06       0  435.87    .055       0  437.41     .06       0
  537.62     .05       0  822.32      .1       0
#XS Ineff= 2 , 0
          352.16  1848.6  396.04         1850.53
Permanent Ineff=
       F       F
Bank Sta=363.8,388
XS Rating Curve= 0 ,0
Exp/Cntr=0.5,0.3

Type RM Length L Ch R = 1 ,9385    ,110.3,91.4,66.3
XS GIS Cut Line= 4
2425680.91249743648697.8133942122425927.50030825648790.241684259
2425938.69931205648941.7564858722426451.12872849 648924.58754302
#Sta/Elev= 30
       0 1977.37    57.5 1965.71    78.8  1960.1   104.5 1950.64   135.9 1937.03
   189.9 1908.35   210.4 1894.73   232.6 1881.71   249.7 1869.42   258.3  1856.3
   260.9 1855.31     276 1853.25   292.1 1853.82   311.8  1852.5  349.991846.752
   352.2  1846.2   360.1 1843.22   368.3 1842.07   392.3 1846.05   423.3    1847
   435.3 1849.21  444.861849.559  544.981857.008   599.4 1860.58  684.991864.471
   751.9 1866.81   775.5 1860.06   787.5 1860.73   876.1 1894.81     928  1913.3
#Mann= 7 ,-1 , 0
       0      .1       0  349.99    .055       0   352.2    .045       0
   392.3    .055       0  444.86     .06       0  544.98     .05       0
  684.99      .1       0
Bank Sta=352.2,392.3
XS Rating Curve= 0 ,0
Exp/Cntr=0.5,0.3

Type RM Length L Ch R = 1 ,9294    ,204.6,185.2,160.1
XS GIS Cut Line= 3
2425582.47067542648841.3757889912425797.34395509648979.349732206
     2426448.882      648964.968
#Sta/Elev= 30
       0 1996.41    24.1  1993.7      901981.218   109.7 1977.31   147.7 1965.07
   255.4 1917.56   292.8 1894.07   309.5 1878.92   324.8 1867.79  331.671858.691
   343.3 1843.75   348.8 1840.36   352.8 1839.99   363.51843.357   368.8 1845.75
  384.581846.089  431.951848.346   460.7 1850.14   492.8 1846.71  532.231848.726
   580.8 1853.33   605.6 1851.39  632.51 1853.73   664.3 1860.92   683.9 1862.67
   704.9 1862.24   720.9 1857.37   732.9 1857.19   796.9 1885.27   907.1 1919.63
#Mann= 9 ,-1 , 0
       0     .12       0      90      .1       0  331.67    .055       0
   343.3    .045       0   363.5    .055       0  384.58     .06       0
  431.95     .06       0  532.23     .05       0  632.51      .1       0
#XS Ineff= 2 , 0
                           463.1         1857.11
Permanent Ineff=
       F       F
Bank Sta=343.3,363.5
XS Rating Curve= 0 ,0
Exp/Cntr=0.5,0.3

Type RM Length L Ch R = 1 ,9109    ,58.5,60.2,66.3
XS GIS Cut Line= 3
2425996.77490404649503.2821883692425910.36227022649058.156644357
2426403.71812148648982.796789276
#Sta/Elev= 30
       0 1882.89   43.681867.119    61.5 1858.69    77.1 1858.87      90 1856.69
   102.3 1860.45   126.7 1871.37  141.281874.891   187.8 1879.27   220.4 1875.02
   262.5 1862.13   304.5 1853.46   339.9  1837.9   346.7 1835.06   354.9 1834.43
   379.3 1837.62   391.6 1840.31   408.1 1841.46   461.9 1843.13   478.1 1842.36
   510.5 1846.72  529.391851.603   586.5 1868.26  628.71  1870.5   660.2 1870.89
  728.031874.932   785.6 1867.06   805.9 1868.66   898.9 1897.41   952.5 1910.94
#Mann= 8 ,-1 , 0
       0     .05       0   43.68      .1       0  141.28     .06       0
   339.9    .045       0   379.3     .06       0  529.39     .06       0
  628.71     .05       0  728.03      .1       0
#XS Ineff= 2 , 0
          329.57    1839  391.17          1839.5
Permanent Ineff=
       F       F
Bank Sta=339.9,379.3
XS Rating Curve= 0 ,0
Exp/Cntr(USF)=0,0
Exp/Cntr=0.5,0.3