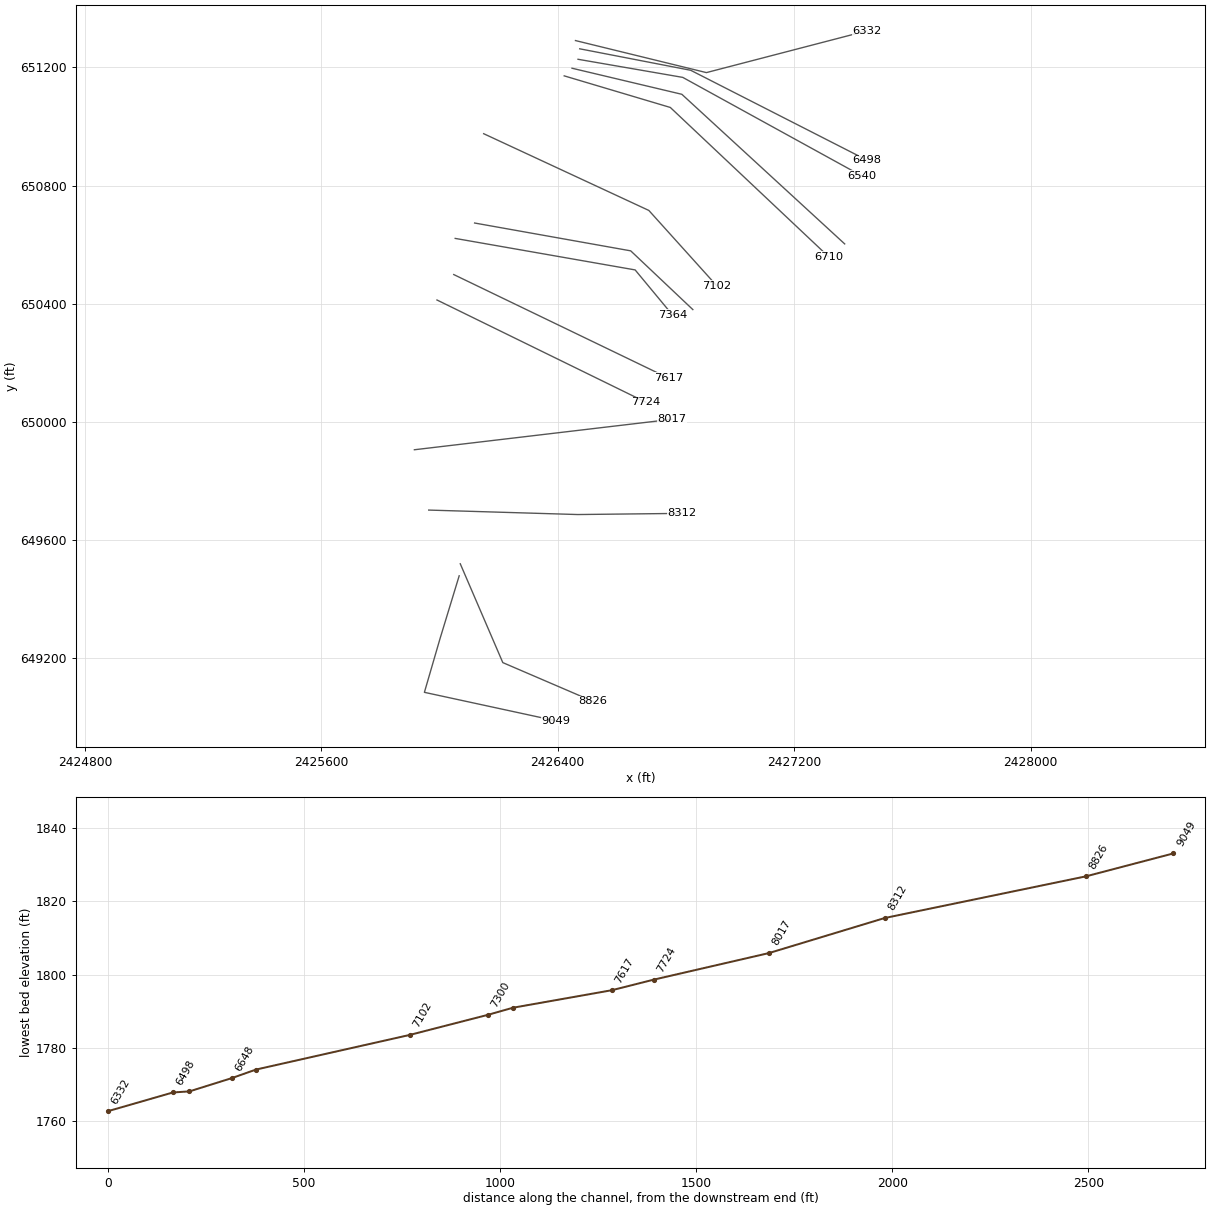
HEC-RAS study MILLCK.prj: MILLCK

--- MILLCK.g01 (geometry) --- (continued)

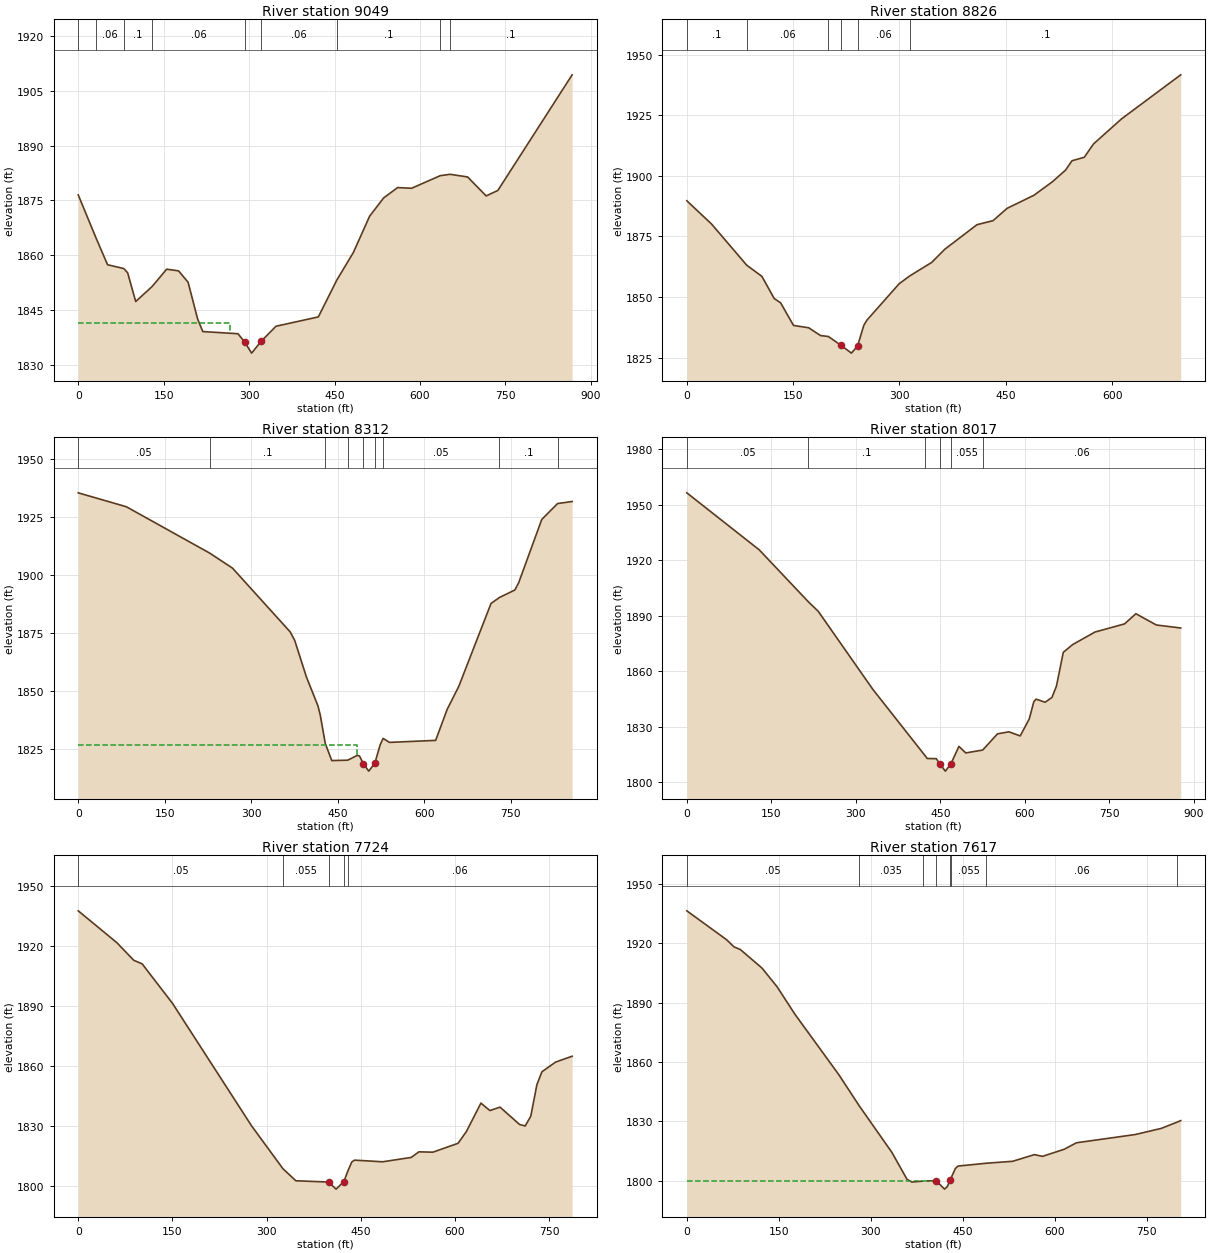
Type RM Length L Ch R = 1 ,9049    ,212.9,222.4,230.9
XS GIS Cut Line= 4
2426066.51840886649479.4372414892426001.79889438649267.154642448
 2425948.8145266649085.128800563 2426394.1412226648988.705280696
#Sta/Elev= 30
       0 1876.49    31.11864.747    51.5 1857.36    79.9 1856.32    86.8 1855.15
   100.9 1847.28  129.631851.377   155.3 1856.15   176.2 1855.68   192.9 1852.57
   209.7 1842.47   218.7 1839.06   280.5 1838.46   292.4 1836.15   304.4 1833.15
   321.4 1836.43   347.2 1840.51   421.6 1843.07  453.881853.124   483.1 1860.72
   511.7 1870.68   536.3 1875.67   560.8 1878.49   585.4 1878.31   635.51881.747
  652.791882.137   683.6 1881.41   716.3 1876.21   736.8 1877.71   867.2 1909.38
#Mann= 9 ,-1 , 0
       0      .1       0    31.1     .06       0    79.9      .1       0
  129.63     .06       0   292.4    .045       0   321.4     .06       0
  453.88      .1       0   635.5     .05       0  652.79      .1       0
#XS Ineff= 2 , 0
          265.69 1841.39
Permanent Ineff=
       F       F
Bank Sta=292.4,321.4
XS Rating Curve= 0 ,0
Exp/Cntr=0.5,0.3

Type RM Length L Ch R = 1 ,8826    ,500,513.8,524.4
XS GIS Cut Line= 3
2426070.19390469649520.1380110592426214.16182398649185.695529451
     2426519.734      649054.369
#Sta/Elev= 30
       0 1889.72    34.9 1880.13   84.511863.155   105.9 1858.55   123.3  1849.4
   132.3 1847.64   150.5 1838.31   171.9 1837.35   188.6 1834.14  199.681833.745
   217.5 1830.11   232.2 1826.89   240.9 1829.86   249.6  1838.3   253.9 1840.44
   299.5  1855.5  314.841858.804   345.4  1864.3   364.1 1869.78   409.3 1879.86
     432 1881.54   451.8 1886.61   489.7    1892   515.9 1897.62   534.2 1902.36
   543.3 1906.23   560.7 1907.67   573.7 1913.17   613.3 1923.52   696.7 1941.67
#Mann= 6 ,-1 , 0
       0      .1       0   84.51     .06       0  199.68     .06       0
   217.5    .045       0   240.9     .06       0  314.84      .1       0
Bank Sta=217.5,240.9
XS Rating Curve= 0 ,0
Exp/Cntr=0.3,0.1

Type RM Length L Ch R = 1 ,8312    ,292.7,295.1,295.5
XS GIS Cut Line= 3
2425963.39265166649701.884752404     2426467.737      649686.763
2426819.39215219 649690.72180171
#Sta/Elev= 30
       0 1935.27    83.4 1929.28  227.891909.323   267.5 1902.84   367.5 1875.39
   375.3 1871.72   395.5 1856.06   415.5  1843.6   419.5  1839.7  428.241827.398
   439.5 1820.02     4671820.172   483.6 1822.22   487.6    1822   494.11818.709
   503.6 1815.47   514.21818.877   523.5 1826.86  528.561829.553   539.6 1827.84
   619.6 1828.71   639.6 1842.07   659.6 1851.89   715.6 1887.64  730.171890.218
   756.9 1893.43   763.6 1896.61   803.6 1923.83  830.971930.649   856.2 1931.53
#Mann= 9 ,-1 , 0
       0     .05       0  227.89      .1       0  428.24     .06       0
     467    .055       0   494.1    .045       0   514.2    .055       0
  528.56     .05       0  730.17      .1       0  830.97     .05       0
#XS Ineff= 2 , 0
          484.03 1826.87
Permanent Ineff=
       F       F
Bank Sta=494.1,514.2
XS Rating Curve= 0 ,0
Exp/Cntr=0.3,0.1

Type RM Length L Ch R = 1 ,8017    ,299.2,293.3,285.8
XS GIS Cut Line= 2
2425914.93773006649906.0325118722426785.79651831650009.003780292
#Sta/Elev= 30
       0 1956.31   128.7 1925.45  215.431897.525   233.4 1892.24   330.1 1850.14
  422.021814.628   426.8 1812.71   442.9 1812.61   449.91809.514     459 1805.88
   468.71809.706   483.1 1819.26   495.2 1815.72  525.311817.271   551.6 1826.03
   571.8 1827.13   591.9 1824.91     608 1834.11   616.1 1843.43   620.1  1844.8
   636.2 1843.11   648.3 1845.72   656.2 1851.77   668.4 1870.09     685 1874.28
   724.6 1881.05   777.2 1885.47   797.3 1890.96   833.6 1884.87   876.9 1883.25
#Mann= 6 ,-1 , 0
       0     .05       0  215.43      .1       0  422.02    .055       0
   449.9    .045       0   468.7    .055       0  525.31     .06       0
Bank Sta=449.9,468.7
XS Rating Curve= 0 ,0
Exp/Cntr=0.3,0.1

Type RM Length L Ch R = 1 ,7724    ,106.8,107.1,106.8
XS GIS Cut Line= 2
2425991.33567725650412.8656174632426697.96115745 650067.03039567
#Sta/Elev= 30
       0 1937.77    61.7  1921.8    88.4 1913.05   101.8 1911.26   150.1 1891.54
   276.1 1830.26  326.191808.778   346.7  1802.8   398.7 1802.16   410.7 1798.62
   423.1  1802.4  429.971808.059   435.8 1812.22   440.2 1813.12   484.8 1812.29
   530.3 1814.46   542.7 1817.27   564.9 1817.09     605 1821.53   618.4 1827.48
   641.4 1841.62   655.8  1837.9   671.8 1839.62     703 1830.95   711.9 1830.19
   720.8 1835.04   730.6 1850.87   738.6 1857.31   760.5 1862.16   786.7 1865.07
#Mann= 5 ,-1 , 0
       0     .05       0  326.19    .055       0   398.7    .045       0
   423.1    .055       0  429.97     .06       0
Bank Sta=398.7,423.1
XS Rating Curve= 0 ,0
Exp/Cntr(USF)=0,0
Exp/Cntr=0.5,0.3

Type RM Length L Ch R = 1 ,7617    ,245.4,252.5,252.9
XS GIS Cut Line= 2
2426048.11534524650498.924966189 2426773.7242516650149.005175574
#Sta/Elev= 30
       0 1936.33    65.1 1921.68    76.9 1918.13    87.3 1916.77   122.8 1907.35
   147.4 1897.89   176.1 1884.18   247.7 1853.64  281.521837.677   334.6 1814.23
   359.2 1800.65   367.1 1799.31  385.121799.773   406.61800.017   420.4 1795.72
   424.8    1797   429.2 1800.08   430.4 1800.95   438.1 1806.19   442.4 1807.37
  488.731808.809   531.4 1809.78   566.9 1813.15   580.2 1812.28   615.8 1815.89
   635.5 1819.14   731.2 1823.29   773.6 1826.38  799.531829.535   805.6 1830.35
#Mann= 8 ,-1 , 0
       0     .05       0  281.52    .035       0  385.12    .055       0
   406.6    .045       0   429.2    .055       0   430.4    .055       0
  488.73     .06       0  799.53    .035       0
#XS Ineff= 2 , 0
          400.85    1800  435.13            1801
Permanent Ineff=
       F       F
Bank Sta=406.6,429.2
XS Rating Curve= 0 ,0
Exp/Cntr=0.5,0.3

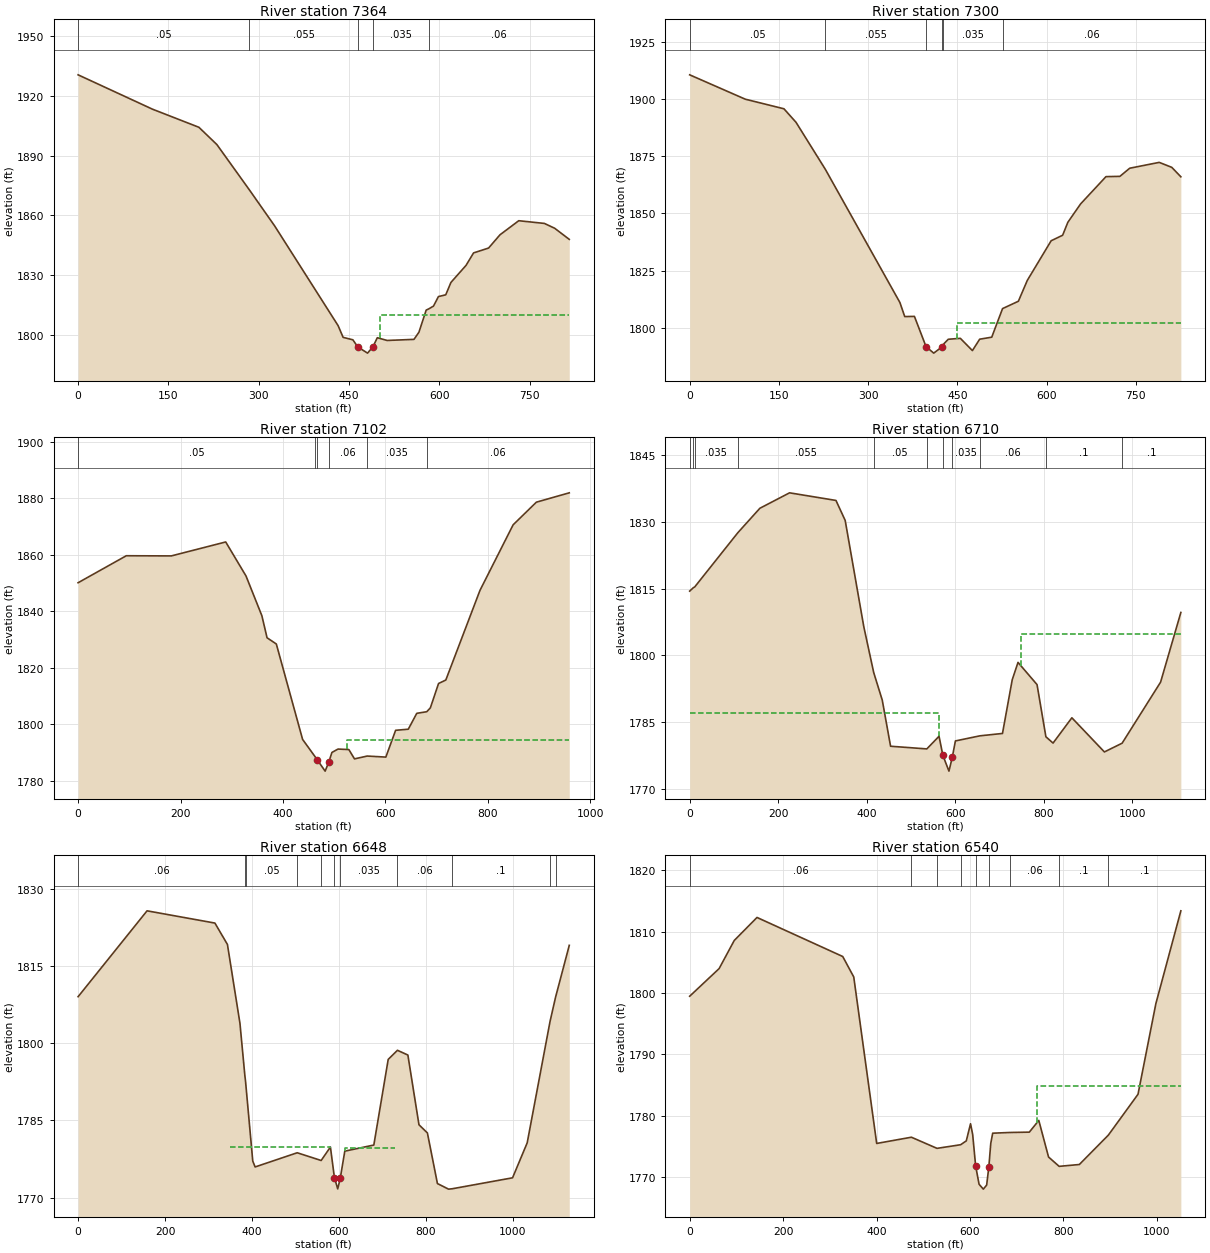
Type RM Length L Ch R = 1 ,7364    ,63,64,62.6
XS GIS Cut Line= 3
2426053.07001105650621.2116969762426661.94066382650514.616369135
2426788.28266983650362.307773557
#Sta/Elev= 30
       0  1930.5   123.5 1913.28   200.7 1904.19   230.6 1895.51  284.58 1872.79
   326.6  1854.7     432 1804.69   440.3 1798.83   456.5  1797.6   464.6 1794.04
   480.9 1790.92   489.81794.095   497.1 1798.65   513.4 1797.27     558 1797.82
   566.2 1801.37   578.3 1812.51  582.56 1813.11   590.5 1814.53   598.6 1819.27
   610.8 1820.17   619.4 1826.37   644.5 1834.93     657 1841.18     682 1843.63
   700.9 1850.27   732.1 1857.33   774.7 1855.97   791.8 1853.54     816 1847.98
#Mann= 5 ,-1 , 0
       0     .05       0  284.58    .055       0   464.6    .045       0
   489.8    .035       0  582.56     .06       0
#XS Ineff= 2 , 0
                          500.91         1810.28
Permanent Ineff=
       F       F
Bank Sta=464.6,489.8
XS Rating Curve= 0 ,0
Exp/Cntr=0.5,0.3

Type RM Length L Ch R = 1 ,7300    ,200.3,198.3,194.3
XS GIS Cut Line= 3
     2426118.742      650673.324 2426647.0193272650579.139447544
2426857.26100297650380.359557798
#Sta/Elev= 30
       0 1910.48    93.5 1899.84   158.5 1895.65   178.8 1889.75   228.11869.223
   353.5 1811.06   361.6 1804.93   377.9 1805.01   397.5 1791.77   410.4 1788.97
   424.1 1791.67  426.761792.874   434.8 1795.02   455.1 1795.43   475.4 1790.08
   487.6 1795.05   507.9 1795.93  526.091808.417   552.7 1811.62   567.7 1820.72
   607.8 1838.03   627.1 1840.44   635.9  1846.1   657.3 1854.11     700 1866.03
   723.4 1866.15   739.9  1869.7   789.5 1872.25   810.6 1870.09   825.9 1865.96
#Mann= 6 ,-1 , 0
       0     .05       0   228.1    .055       0   397.5    .045       0
   424.1    .055       0  426.76    .035       0  526.09     .06       0
#XS Ineff= 2 , 0
                          449.69         1802.12
Permanent Ineff=
       F       F
Bank Sta=397.5,424.1
XS Rating Curve= 0 ,0
Exp/Cntr=0.3,0.1

Type RM Length L Ch R = 1 ,7102    ,398.9,392.5,390.9
XS GIS Cut Line= 3
2426149.38947529650975.5932438372426708.35052471650715.868483503
     2426937.762      650461.431
#Sta/Elev= 30
       0 1850.09    94.1 1859.63     182 1859.57   288.2  1864.5   327.9 1852.45
   358.8 1838.42   368.9 1830.63     387 1828.44   438.3 1794.71   462.11788.739
   466.8 1787.52   482.3  1783.5   489.81786.862   495.5  1790.1   507.5  1791.3
   528.6 1791.12   539.6 1787.83  564.441788.826   600.8 1788.46   619.9 1797.93
   644.6 1798.32   661.2 1803.93  680.65  1804.5   687.7 1805.86   703.7 1814.47
   717.9  1815.7   784.6  1847.4   849.3 1870.56   894.7 1878.57   958.9 1881.87
#Mann= 6 ,-1 , 0
       0     .05       0   462.1     .06       0   466.8    .045       0
   489.8     .06       0  564.44    .035       0  680.65     .06       0
#XS Ineff= 2 , 0
                          525.34         1794.52
Permanent Ineff=
       F       F
Bank Sta=466.8,489.8
XS Rating Curve= 0 ,0
Exp/Cntr=0.3,0.1

Type RM Length L Ch R = 1 ,6710    ,62.4,62.1,62
XS GIS Cut Line= 3
     2426421.926      651171.3052426781.01447309651064.393615844
2427316.04098575650559.988498397
#Sta/Elev= 30
       0 1814.44    8.571815.228   11.351815.374  108.72 1827.54   158.6 1833.04
   225.7 1836.51   330.6  1834.8   351.4 1830.32   393.5 1806.43  415.961796.114
   435.2 1789.96     454  1779.6  535.911778.999   563.5 1781.84   572.2 1777.55
   585.9 1774.01   593.4 1777.09   600.5 1780.79  655.851781.936   706.9 1782.47
   728.9 1794.52     742 1798.43     785 1793.44     8051781.725   821.2 1780.31
   863.7 1785.99   937.2 1778.32  977.281780.283  1064.2 1793.99    1110 1809.64
#Mann= 11 ,-1 , 0
       0    .055       0    8.57     .06       0   11.35    .035       0
  108.72    .055       0  415.96     .05       0  535.91    .035       0
   572.2    .045       0   593.4    .035       0  655.85     .06       0
     805      .1       0  977.28      .1       0
#XS Ineff= 2 , 0
          563.22 1786.98  749.08         1804.87
Permanent Ineff=
       F       F
Bank Sta=572.2,593.4
XS Rating Curve= 0 ,0
Exp/Cntr=0.5,0.3

Type RM Length L Ch R = 1 ,6648    ,104.3,107.5,112.1
XS GIS Cut Line= 3
      2426448.36      651197.1312426820.03925721651108.909137644
2427371.14397292650602.587853508
#Sta/Elev= 30
       0 1809.06   158.7 1825.75   314.9 1823.37   343.7 1819.21   372.5 1803.89
   383.81793.745  385.361792.623     402 1777.11   407.4 1775.97  504.271778.728
  559.391777.225   580.7 1779.84   589.91773.912   597.5 1771.71   603.3 1773.74
   613.8 1779.04   680.6 1780.23   713.7 1796.87  734.981798.644     759 1797.72
   784.5 1784.17   803.9 1782.58     827 1772.74   852.5 1771.66  861.02 1771.73
   999.9 1773.86  1033.6 1780.66 1086.161804.248 1098.851808.955  1130.4 1819.04
#Mann= 11 ,-1 , 0
       0     .06       0   383.8    .055       0  385.36     .05       0
  504.27     .06       0  559.39    .035       0   589.9    .045       0
   603.3    .035       0  734.98     .06       0  861.02      .1       0
 1086.16      .1       0 1098.85      .1       0
#XS Ineff= 3 ,-1
  349.34  580.871779.767  614.14     7301779.601     730    1100    1782
Permanent Ineff=
       F       F       F
Bank Sta=589.9,603.3
XS Rating Curve= 0 ,0
Exp/Cntr=0.5,0.3

Type RM Length L Ch R = 1 ,6540    ,41.6,42,42.9
XS GIS Cut Line= 3
     2426468.696      651227.4112426823.12301199651166.132995133
2427429.17249816650832.715002137
#Sta/Elev= 30
       0 1799.46      63 1803.96    95.4 1808.54   144.1 1812.29   327.6 1805.93
   351.2  1802.6   400.3 1775.48  474.581776.495  529.431774.682  580.011775.271
   592.1  1775.9   601.2 1778.69   605.8 1776.93   612.1 1771.82   619.5 1768.83
   628.6 1768.04   635.7  1768.7   640.3  1771.6   644.5 1775.49   648.6 1777.15
  685.441777.267     727 1777.32   747.3 1779.23   768.2 1773.27  790.87 1771.75
   834.1 1772.05   896.31776.845   959.7 1783.49   997.9 1798.25  1051.4 1813.37
#Mann= 9 ,-1 , 0
       0     .06       0  474.58    .035       0  529.43     .06       0
  580.01    .035       0   612.1    .045       0   640.3    .035       0
  685.44     .06       0  790.87      .1       0   896.3      .1       0
#XS Ineff= 2 , 0
                          742.92         1784.87
Permanent Ineff=
       F       F
Bank Sta=612.1,640.3
XS Rating Curve= 0 ,0
Exp/Cntr=0.5,0.3

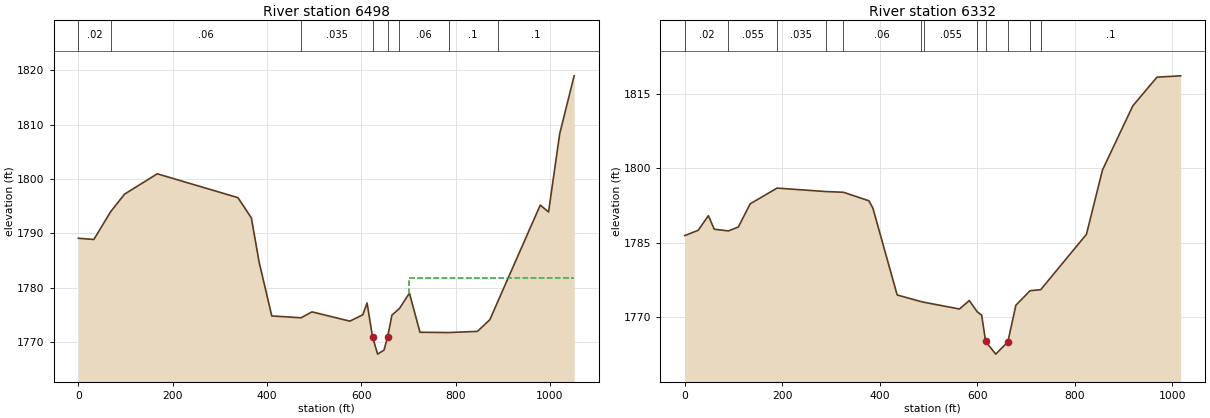
Type RM Length L Ch R = 1 ,6498    ,155.1,166.3,180.2
XS GIS Cut Line= 3
      2426474.44      651262.8772426850.09051169651190.158000712
2427446.00399964650886.242021963
#Sta/Elev= 30
       0 1789.08    32.9 1788.86   68.641793.983    98.1 1797.21   167.4 1800.95
   338.5 1796.56     367 1792.83   383.4 1784.71   410.3 1774.78  472.381774.441
   495.6 1775.53   575.9 1773.82   603.4    1775   612.4 1777.17   624.1 1770.87
   634.8 1767.75   648.3 1768.49   656.1 1770.94   665.1 1774.93  681.021776.146
   702.2 1778.98   724.6 1771.78  785.33 1771.72   846.5 1771.94   872.8 1774.09
  889.651777.424   979.7 1795.19   997.3 1793.92    1021 1808.35  1051.6 1818.99
#Mann= 8 ,-1 , 0
       0     .02       0   68.64     .06       0  472.38    .035       0
   624.1    .045       0   656.1    .035       0  681.02     .06       0
  785.33      .1       0  889.65      .1       0
#XS Ineff= 2 , 0
                          701.12         1781.77
Permanent Ineff=
       F       F
Bank Sta=624.1,656.1
XS Rating Curve= 0 ,0
Exp/Cntr=0.3,0.1

Type RM Length L Ch R = 1 ,6332    ,416.4,423,430.1
XS GIS Cut Line= 3
     2426460.072      651290.7542426903.13722644651182.336284063
2427445.65215754651323.493568839
#Sta/Elev= 30
       0 1786.46    27.5 1787.53    48.4 1790.46    60.4 1787.74   89.561787.395
   109.8 1788.19   134.1 1792.85  189.191796.015  288.82 1795.32  325.251795.175
   377.5 1793.46   385.7 1791.98   435.5 1774.51  484.38 1773.18  490.931773.036
   563.2 1771.69   583.3 1773.39  599.481771.142   608.7 1770.46   616.9 1765.16
   637.6 1762.61   662.4 1765.07   678.9 1772.45  708.021775.368  729.811775.575
   823.6 1786.72   856.4 1799.64   918.6 1812.55   968.2 1818.33  1016.7  1818.6
#Mann= 12 ,-1 , 0
       0     .02       0   89.56    .055       0  189.19    .035       0
  288.82    .055       0  325.25     .06       0  484.38    .035       0
  490.93    .055       0  599.48     .06       0   616.9    .045       0
   662.4     .06       0  708.02      .1       0  729.81      .1       0
Bank Sta=616.9,662.4
XS Rating Curve= 0 ,0
Exp/Cntr=0.3,0.1