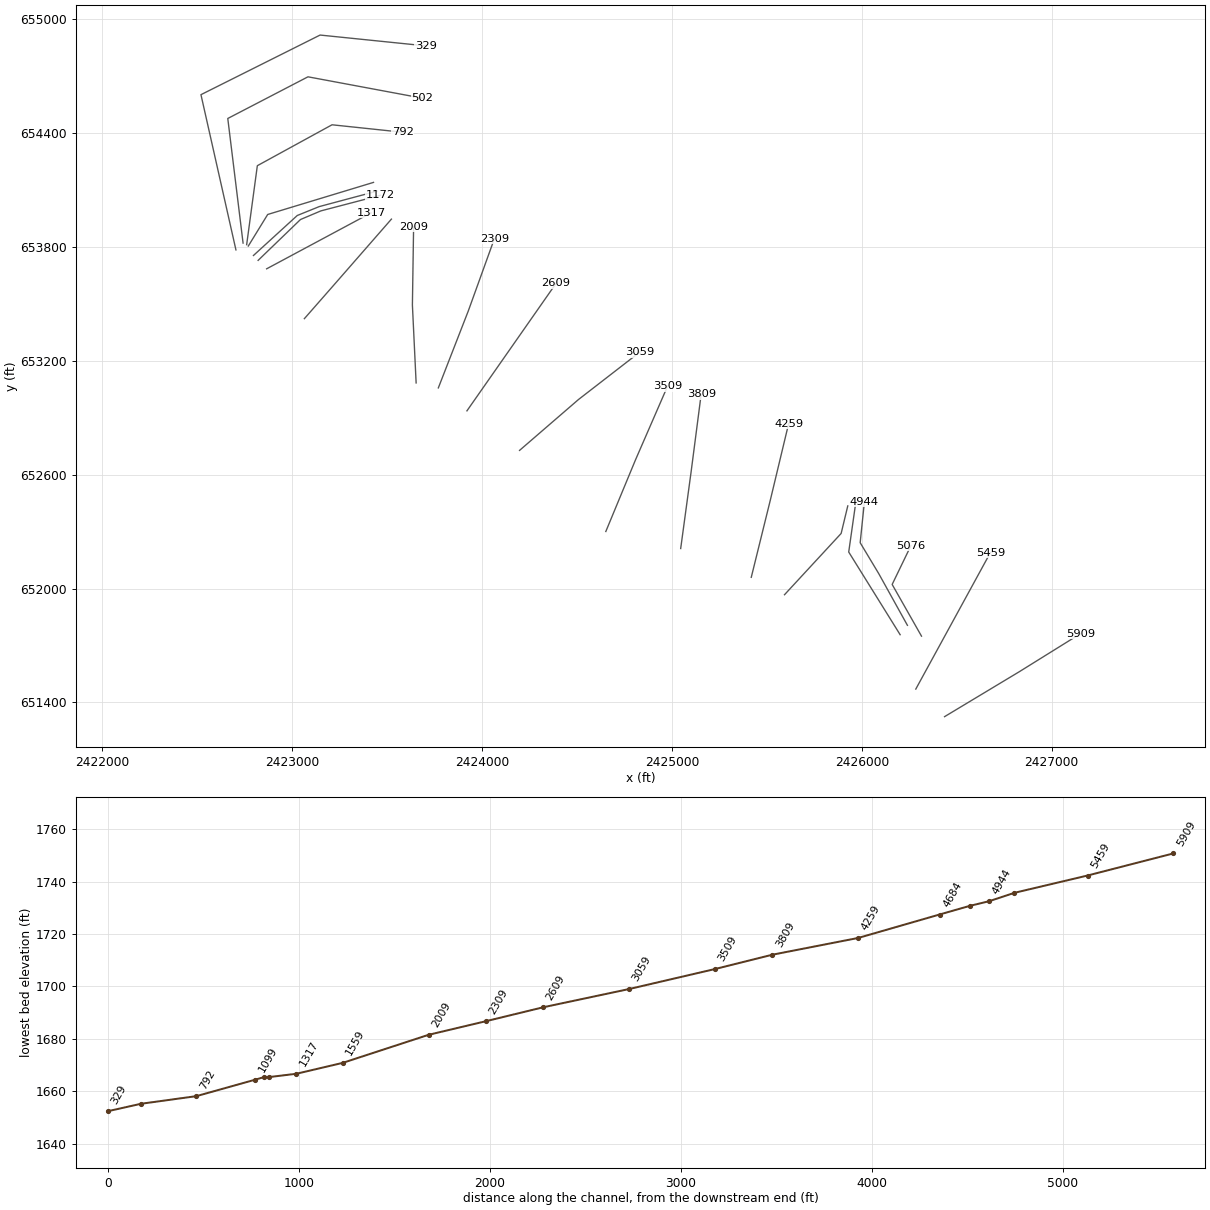
HEC-RAS study MILLCK.prj: MILLCK

--- MILLCK.g01 (geometry) --- (continued)

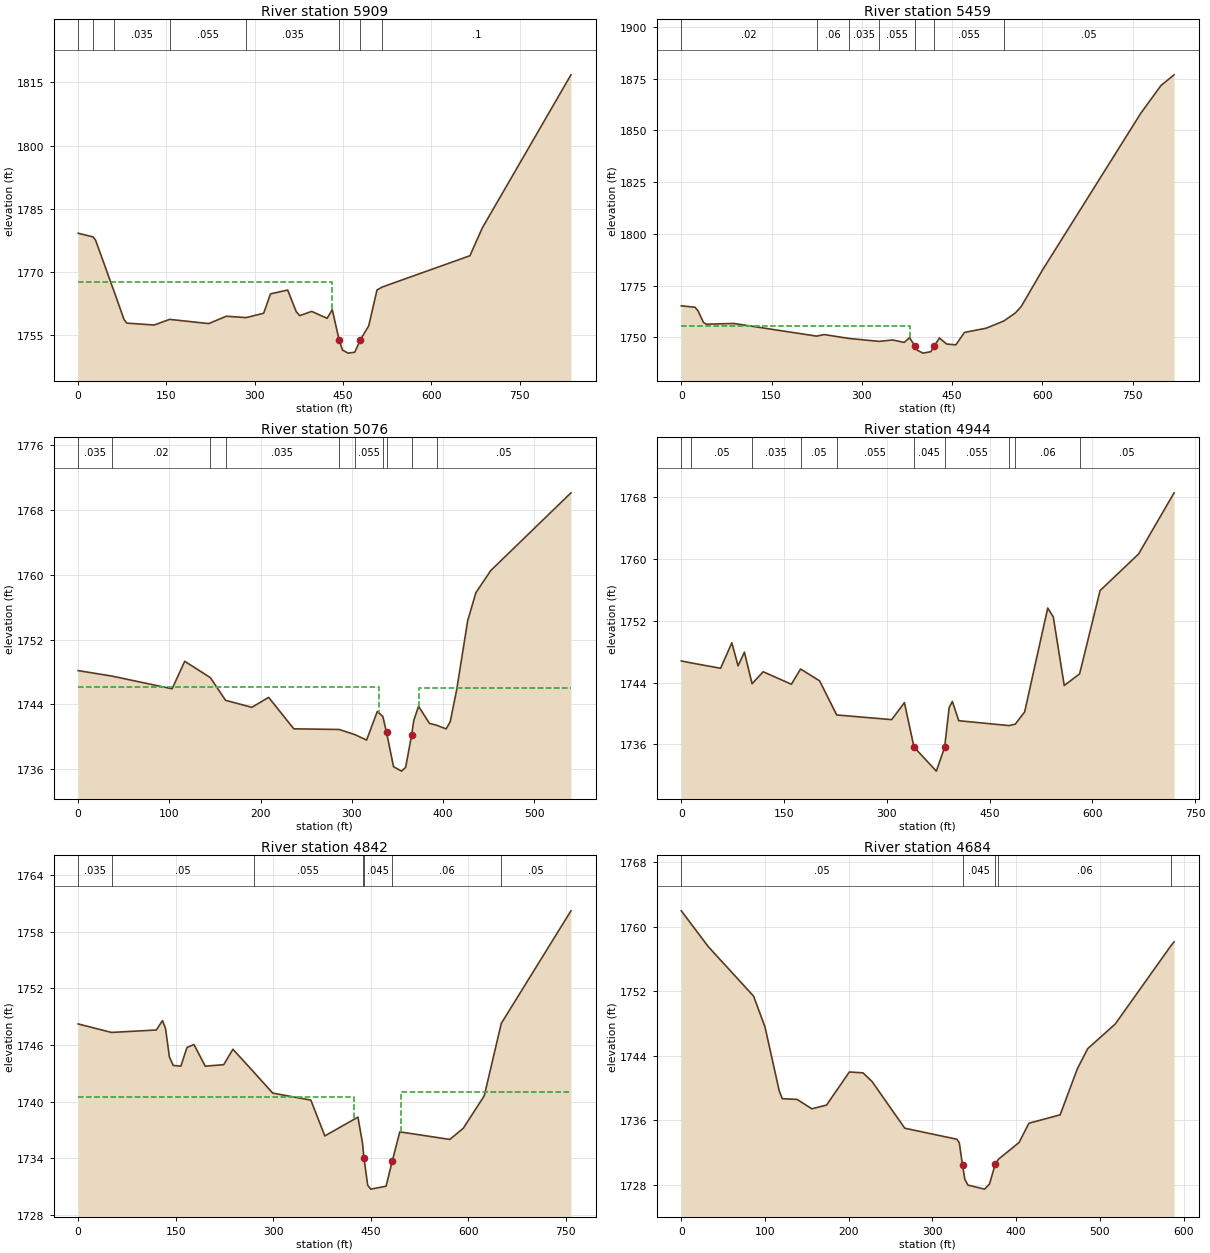
Type RM Length L Ch R = 1 ,5909    ,440.9,450,459.3
XS GIS Cut Line= 3
2426435.93444398651325.188224069     2426828.981      651561.551
2427150.59333432651761.576000594
#Sta/Elev= 30
       0 1779.21   25.281778.346    29.5  1777.6   61.381765.277      78 1758.73
    82.6  1757.9   129.3 1757.45  155.371758.785   221.9 1757.79   251.7 1759.53
  285.461759.208   315.2 1760.24   326.8 1764.83     356 1765.75   370.5 1760.64
   376.4 1759.67   396.8 1760.68     423 1759.04   431.8 1761.08   443.4 1753.94
   449.2 1751.51   458.6 1750.78   470.1    1751   479.6 1753.98   493.7 1757.24
   507.8 1765.76  516.951766.473   665.7 1773.88   686.8 1780.49   837.4 1816.79
#Mann= 8 ,-1 , 0
       0    .055       0   25.28     .02       0   61.38    .035       0
  155.37    .055       0  285.46    .035       0   443.4    .045       0
   479.6    .035       0  516.95      .1       0
#XS Ineff= 2 , 0
          431.44 1767.66
Permanent Ineff=
       F       F
Bank Sta=443.4,479.6
XS Rating Curve= 0 ,0
Exp/Cntr=0.3,0.1

Type RM Length L Ch R = 1 ,5459    ,382.9,382.6,383.5
XS GIS Cut Line= 3
     2426284.401      651470.469     2426480.803      651829.797
     2426677.205      652189.125
#Sta/Elev= 30
       0  1765.2    22.7 1764.53    27.8  1762.8    36.9 1757.15    41.5 1756.33
    87.5 1756.66  224.981750.547   237.5 1751.31  278.731749.428  328.671748.001
   351.5 1748.69   370.5 1747.51   379.3  1749.8   388.2 1745.84   392.5 1743.69
   401.6 1742.33   414.7 1743.01   420.6 1745.81     429 1749.64   441.2 1746.72
   456.3 1746.34   470.7 1752.34   506.5 1754.36  536.031757.866   555.3 1761.78
     565 1764.88   600.4 1782.55   763.8 1858.36   797.2 1871.71     819 1876.89
#Mann= 7 ,-1 , 0
       0     .02       0  224.98     .06       0  278.73    .035       0
  328.67    .055       0   388.2    .045       0   420.6    .055       0
  536.03     .05       0
#XS Ineff= 2 , 0
          380.32 1755.44
Permanent Ineff=
       F       F
Bank Sta=388.2,420.6
XS Rating Curve= 0 ,0
Exp/Cntr=0.3,0.1

Type RM Length L Ch R = 1 ,5076    ,112.9,132.4,150.1
XS GIS Cut Line= 3
2426314.38259999651749.2787135582426159.87012712652021.516961864
2426258.76065509652226.081496612
#Sta/Elev= 30
       0 1748.16    37.11747.479     103 1745.91   116.8 1749.31  144.931747.288
  161.571744.486   190.4 1743.62   208.8 1744.85   236.4 1740.96  286.05 1740.88
  303.471740.239   316.2 1739.57   327.9 1743.11     3341742.482     338 1740.54
   345.7 1736.28   354.5 1735.73     359  1736.2   365.6 1740.23   367.9    1742
   373.1 1743.75   385.1 1741.63   392.91741.409   403.4 1740.95   407.9 1741.85
     415 1745.84     427 1754.33     436  1757.8   452.3 1760.53   540.2 1770.14
#Mann= 10 ,-1 , 0
       0    .035       0    37.1     .02       0  144.93     .05       0
  161.57    .035       0  286.05     .06       0  303.47    .055       0
     334     .06       0     338    .045       0   365.6     .06       0
   392.9     .05       0
#XS Ineff= 2 , 0
          330.16 1746.13  373.49         1745.98
Permanent Ineff=
       F       F
Bank Sta=338,365.6
XS Rating Curve= 0 ,0
Exp/Cntr=0.5,0.3

Type RM Length L Ch R = 1 ,4944    ,108.2,101.6,107.9
XS GIS Cut Line= 4
2426240.23303459651806.3678960472426089.17458649652078.630490673
2425991.40286855652241.3492570442426013.81338938652458.339889747
#Sta/Elev= 30
       0  1746.8   13.671746.556    57.4 1745.85    73.8 1749.15    82.9 1746.16
    92.1 1747.94  103.321743.847   119.5  1745.4   160.7 1743.78  174.151745.755
   201.9 1744.22  226.851739.804   307.1  1739.2   325.7  1741.4   339.7 1735.64
   372.3 1732.53   384.41735.612     391 1740.76   395.7 1741.55     405 1739.06
  478.491738.426  487.511738.616   501.2  1740.2   534.9 1753.65     543  1752.5
     559 1743.62   581.41745.125   611.3 1755.91   667.6 1760.66   719.3 1768.57
#Mann= 10 ,-1 , 0
       0     .02       0   13.67     .05       0  103.32    .035       0
  174.15     .05       0  226.85    .055       0   339.7    .045       0
   384.4    .055       0  478.49     .05       0  487.51     .06       0
   581.4     .05       0
#XS Ineff= 2 , 0
           326.9  1740.3  391.79          1739.5
Permanent Ineff=
       F       F
Bank Sta=339.7,384.4
XS Rating Curve= 0 ,0
Exp/Cntr=0.5,0.3

Type RM Length L Ch R = 1 ,4842    ,173.5,158,126
XS GIS Cut Line= 3
2426201.94048439651756.8279992882425931.05650231652192.372497329
2425965.57500926652434.815504214
#Sta/Elev= 30
       0 1748.22   51.291747.321   120.2 1747.58   129.6 1748.57   134.3 1747.75
   140.3 1744.74   146.1 1743.83   157.9 1743.75   167.3 1745.73   178.1 1746.04
   195.4 1743.75   223.8 1743.91     238 1745.54  269.651743.155   299.2  1740.9
   357.8 1740.16   379.3 1736.37   430.2 1738.36  437.311735.576   439.5 1734.03
   445.2 1731.16   449.9 1730.74   473.5 1731.05     483  1733.7   494.6  1736.8
   571.5    1736   592.2 1737.18   624.5 1740.62  650.691748.281   757.8 1760.19
#Mann= 7 ,-1 , 0
       0    .035       0   51.29     .05       0  269.65    .055       0
  437.31     .06       0   439.5    .045       0     483     .06       0
  650.69     .05       0
#XS Ineff= 2 , 0
           423.4 1740.52   495.8         1740.97
Permanent Ineff=
       F       F
Bank Sta=439.5,483
XS Rating Curve= 0 ,0
Exp/Cntr=0.5,0.3

Type RM Length L Ch R = 1 ,4684    ,413.7,425.4,432.3
XS GIS Cut Line= 3
2425592.84033135651967.4588873722425891.16576263 652290.19595846
2425926.09556492652435.286783054
#Sta/Elev= 30
       0 1761.99    32.3 1757.54    86.4  1751.4     100 1747.58     117 1739.65
   120.7 1738.67   138.3 1738.59     156 1737.42   173.5 1737.88   200.8 1741.99
   217.1 1741.88     228 1740.79     267 1735.01   329.3 1733.64   332.1 1733.21
     3361730.413   338.7 1728.69   342.4 1727.95   362.3 1727.45   368.2 1728.08
   375.1 1730.56  378.871731.161   403.5 1733.23   415.3 1735.63   452.6 1736.67
   473.1 1742.37   485.5 1744.88   518.4 1747.94  584.751757.631   588.7 1758.14
#Mann= 5 ,-1 , 0
       0     .05       0     336    .045       0   375.1     .05       0
  378.87     .06       0  584.75     .05       0
Bank Sta=336,375.1
XS Rating Curve= 0 ,0
Exp/Cntr=0.3,0.1

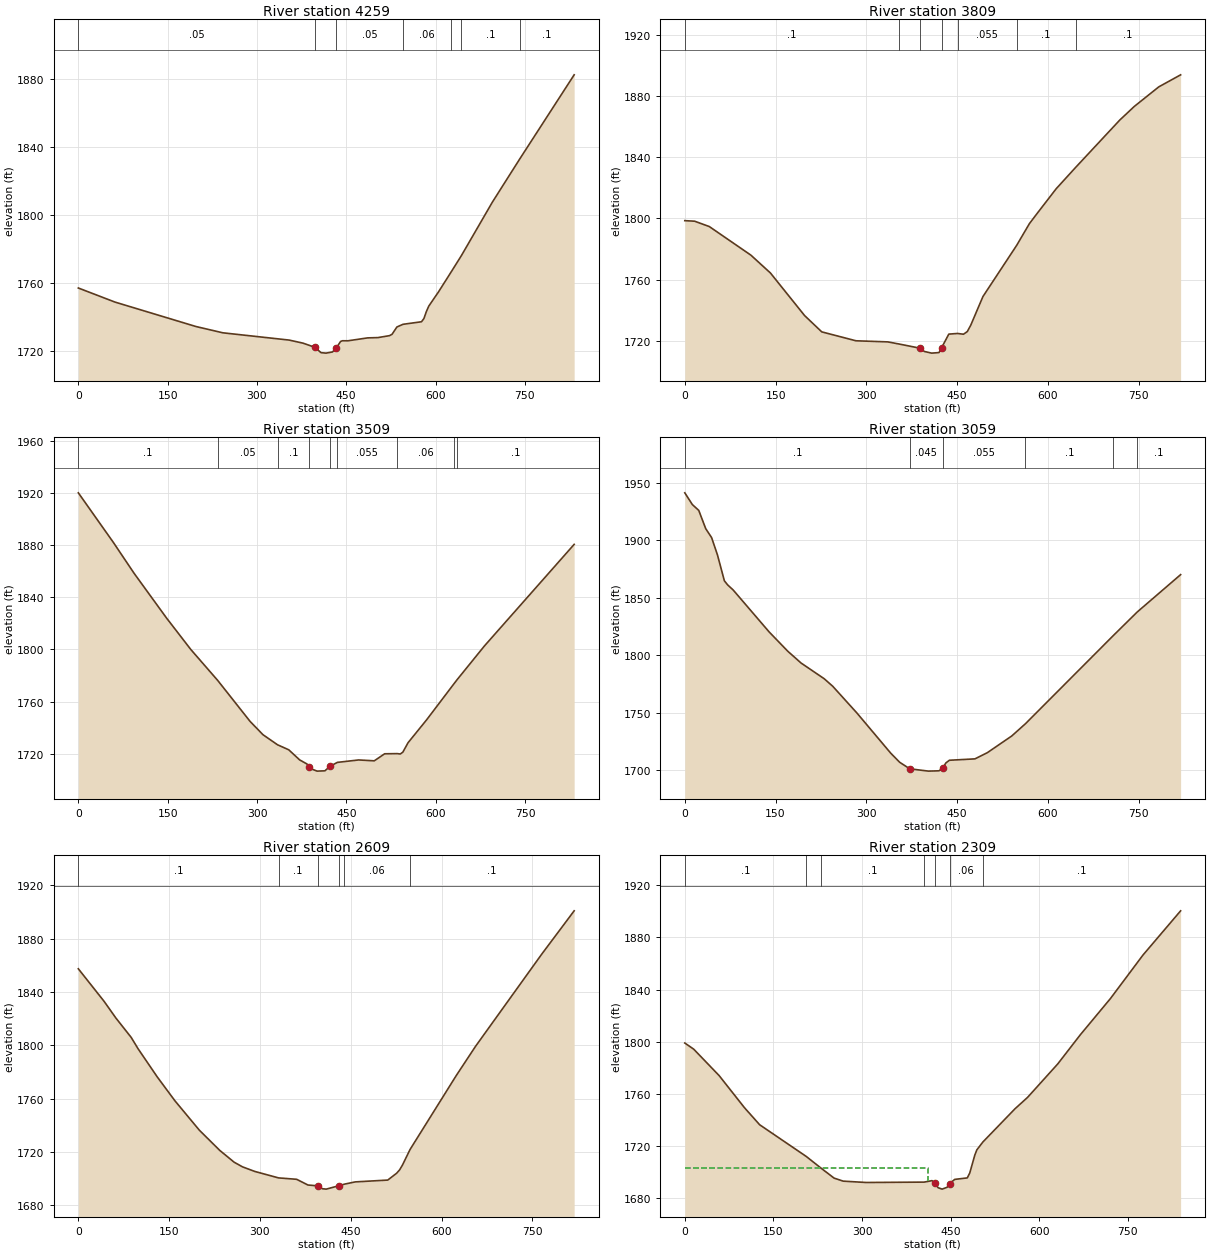
Type RM Length L Ch R = 1 ,4259    ,447.1,450,451.1
XS GIS Cut Line= 3
2425417.72983239652059.060700566      2425518.01       652465.29
     2425614.573      652868.388
#Sta/Elev= 30
       0 1756.84    61.6 1748.55   197.6 1734.17   242.9 1730.46   354.2 1726.19
   377.4 1724.39   397.2 1721.96   407.7 1718.78     416 1718.51     427  1719.2
   433.6 1721.71   440.6 1725.39   443.6 1725.78     453 1725.77   485.9 1727.48
   503.3 1727.65   522.9 1728.81     527  1729.6   535.2 1733.91  545.411735.476
   576.4 1736.97   580.5 1738.84   584.6 1742.93   588.7 1746.19   605.2 1754.64
  625.421765.817  643.271775.782   695.4 1807.31  741.12 1832.59   832.9 1882.32
#Mann= 7 ,-1 , 0
       0     .05       0   397.2    .045       0   433.6     .05       0
  545.41     .06       0  625.42    .055       0  643.27      .1       0
  741.12      .1       0
Bank Sta=397.2,433.6
XS Rating Curve= 0 ,0
Exp/Cntr=0.3,0.1

Type RM Length L Ch R = 1 ,3809    ,305.2,300,295.8
XS GIS Cut Line= 3
     2425046.013      652210.777     2425101.129      652616.549
     2425153.815      653022.655
#Sta/Elev= 30
       0 1798.59    16.3 1798.22    40.5 1794.73   109.1 1776.09   141.4 1764.44
   197.9 1736.62   226.2 1725.98   282.7 1720.16   335.2 1719.44  353.061718.115
   388.1 1715.36   395.7 1713.18   407.8  1712.1   419.9 1712.46   424.2 1715.63
   436.1 1724.51  450.621724.933   460.3 1724.44   466.6 1726.15   472.4 1730.39
   492.5 1749.06  548.191782.457   569.2 1796.61   580.8 1802.68   613.5 1819.44
  645.761833.423   718.4 1864.22   742.6 1873.19   782.9 1885.92     819 1893.79
#Mann= 7 ,-1 , 0
       0      .1       0  353.06     .05       0   388.1    .045       0
   424.2     .05       0  450.62    .055       0  548.19      .1       0
  645.76      .1       0
Bank Sta=388.1,424.2
XS Rating Curve= 0 ,0
Exp/Cntr=0.3,0.1

Type RM Length L Ch R = 1 ,3509    ,458.4,450,441.9
XS GIS Cut Line= 3
2424651.62560355652300.450132149      2424807.77      652677.355
2424977.18482797653066.665579661
#Sta/Elev= 30
       0 1920.12    58.9 1882.02    93.6 1858.41   148.1 1824.08   188.8 1799.98
  234.041776.203   288.4 1744.78     310 1734.59  334.421726.865   353.3    1723
   371.6 1715.26   383.7 1712.17     388  1710.1   392.3 1708.14     401 1706.64
     414 1706.88   422.7 1710.35  434.921713.347   470.7 1715.21   496.9 1714.54
   514.3 1719.94  535.751720.068   540.5 1719.78   544.9 1721.21   553.6 1728.42
   584.7 1745.95  631.311774.014  636.571777.125   681.9 1802.68   832.5 1880.58
#Mann= 9 ,-1 , 0
       0      .1       0  234.04     .05       0  334.42      .1       0
     388    .045       0   422.7      .1       0  434.92    .055       0
  535.75     .06       0  631.31      .1       0  636.57      .1       0
Bank Sta=388,422.7
XS Rating Curve= 0 ,0
Exp/Cntr=0.3,0.1

Type RM Length L Ch R = 1 ,3059    ,441.3,450,454.7
XS GIS Cut Line= 3
     2424197.246      652727.609     2424507.755      652995.671
      2424831.48      653246.249
#Sta/Elev= 30
       0 1941.33    12.5  1931.1    23.1 1926.03    34.6 1910.11    44.3 1902.36
      54 1887.27    65.4 1864.77    70.7 1861.24      80 1856.69   139.5 1820.17
   170.3 1803.37   192.2 1793.13   230.3  1779.5   244.5 1772.92   284.2  1749.8
   340.2 1714.77   355.1 1706.75   371.9 1701.01   402.9    1699   420.3 1699.28
     426 1701.59   431.7 1706.19   437.4 1708.46   479.7 1709.68     500 1715.03
   540.4 1729.58  563.061740.255  708.551817.142  747.931837.595   819.6 1870.09
#Mann= 6 ,-1 , 0
       0      .1       0   371.9    .045       0     426    .055       0
  563.06      .1       0  708.55      .1       0  747.93      .1       0
Bank Sta=371.9,426
XS Rating Curve= 0 ,0
Exp/Cntr=0.3,0.1

Type RM Length L Ch R = 1 ,2609    ,296.7,300,302
XS GIS Cut Line= 3
     2423920.157      652935.975     2424154.783      653271.595
      2424389.41      653607.214
#Sta/Elev= 30
       0  1857.3    42.6 1832.86    62.1 1820.33    87.3 1805.84    98.6 1797.38
   130.3 1776.24   159.7  1758.2     200 1736.19   233.7 1721.05   257.3 1712.25
   271.1 1708.75   291.5 1705.29  330.731700.457   360.6  1699.4   379.4  1695.1
   395.5  1694.5   403.2 1692.32   409.4 1692.03   430.4 1694.57  439.361695.747
   457.4 1697.45   511.1 1698.82   525.8 1703.97   530.7 1706.49   535.4 1710.08
  547.991721.793   624.4 1777.32     656 1799.06   765.1 1868.06     819 1900.77
#Mann= 6 ,-1 , 0
       0      .1       0  330.73      .1       0   395.5    .045       0
   430.4      .1       0  439.36     .06       0  547.99      .1       0
Bank Sta=395.5,430.4
XS Rating Curve= 0 ,0
Exp/Cntr=0.3,0.1

Type RM Length L Ch R = 1 ,2309    ,294.7,300,304.8
XS GIS Cut Line= 3
2423769.49249852653056.828000594      2423927.19      653461.865
     2424064.654       653842.71
#Sta/Elev= 30
       0 1798.92    15.1 1794.21    58.2 1773.88   100.9 1749.32   126.7 1736.17
  205.481711.861   231.31702.613   252.8 1695.16   268.3 1692.84     307 1691.81
  405.241692.099   418.6 1693.22   422.9 1691.78   428.9 1687.79   435.7 1686.71
   444.2 1688.14   448.5 1691.01   457.1 1694.19   478.3 1695.33   482.5 1699.13
     491 1712.81   494.5 1716.88  504.761722.932   559.1 1748.43   580.3 1757.15
   631.4 1782.83   669.6 1805.22   720.7  1833.1   775.7 1866.46   839.5 1900.46
#Mann= 7 ,-1 , 0
       0      .1       0  205.48      .1       0   231.3      .1       0
  405.24     .06       0   422.9    .045       0   448.5     .06       0
  504.76      .1       0
#XS Ineff= 2 , 0
          411.76 1702.66
Permanent Ineff=
       F       F
Bank Sta=422.9,448.5
XS Rating Curve= 0 ,0
Exp/Cntr=0.3,0.1

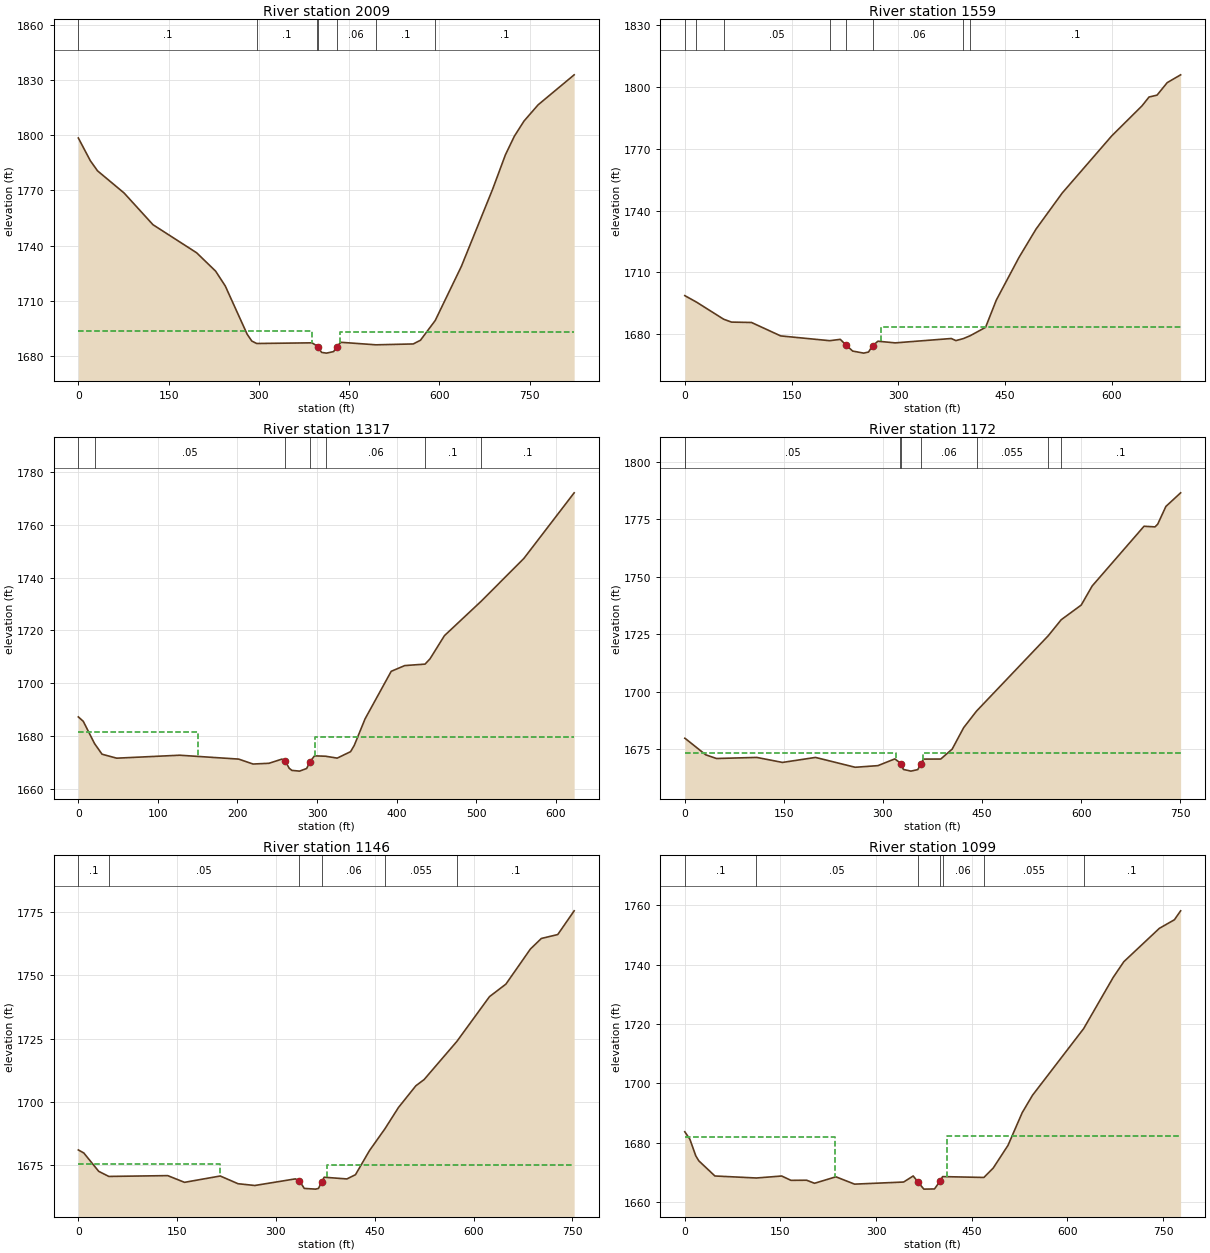
Type RM Length L Ch R = 1 ,2009    ,464.2,450,439
XS GIS Cut Line= 3
     2423652.513      653083.024      2423632.87      653493.601
     2423639.238      653906.313
#Sta/Elev= 30
       0  1798.5    19.9 1786.16    31.9 1780.63      76 1768.59     124 1751.35
   196.5 1736.09   228.1  1726.1   244.1 1718.06   280.5  1691.8   288.2 1688.09
  296.281686.756   388.3 1687.12  395.841685.556   397.6  1684.8   404.3 1681.91
   412.3 1681.52   424.3 1682.38   429.11685.046   436.3 1687.41  494.491686.037
   556.4 1686.51   568.4 1688.51  592.971699.267   636.4 1728.68   688.4 1770.69
   709.6 1789.36   724.4 1799.42   740.4 1807.66   763.9 1816.51   823.8 1832.83
#Mann= 7 ,-1 , 0
       0      .1       0  296.28      .1       0  395.84     .06       0
   397.6    .045       0   429.1     .06       0  494.49      .1       0
  592.97      .1       0
#XS Ineff= 2 , 0
          389.06 1693.64  434.83          1693.2
Permanent Ineff=
       F       F
Bank Sta=397.6,429.1
XS Rating Curve= 0 ,0
Exp/Cntr=0.3,0.1

Type RM Length L Ch R = 1 ,1559    ,250.2,242,237.1
XS GIS Cut Line= 3
2423063.87950407653421.589925548     2423229.564      653610.511
     2423522.387      653945.876
#Sta/Elev= 30
       0 1698.72   16.411695.579    54.6 1687.26    65.6 1685.87    93.7 1685.68
   134.7 1679.16  203.611676.837   218.4 1677.49   226.9 1674.61   235.8  1671.8
   251.3  1670.8   258.1 1671.33   263.7 1674.35   271.3 1676.58   295.6 1675.78
   374.3  1677.9   380.8 1676.88   391.3 1677.86  401.021679.273   422.5 1683.33
   437.6 1696.56   469.5  1717.3   493.4 1731.03   530.2 1748.55   599.7 1776.27
   642.3 1790.88   652.1 1795.15   663.4 1796.07   677.6 1802.12   696.5 1805.93
#Mann= 8 ,-1 , 0
       0     .05       0   16.41      .1       0    54.6     .05       0
  203.61     .06       0   226.9    .045       0   263.7     .06       0
   391.3      .1       0  401.02      .1       0
#XS Ineff= 2 , 0
                          275.14         1683.45
Permanent Ineff=
       F       F
Bank Sta=226.9,263.7
XS Rating Curve= 0 ,0
Exp/Cntr=0.3,0.1

Type RM Length L Ch R = 1 ,1317    ,148,145.2,145.2
XS GIS Cut Line= 2
2422865.18303884653684.106464826 2423414.3824567653978.466450581
#Sta/Elev= 30
       0 1687.21     6.2 1685.54   20.371677.097    29.8 1673.06    48.2 1671.56
   127.3 1672.68   201.5 1671.21   219.6 1669.34   239.6 1669.62   255.9 1671.21
   260.3 1670.33     265 1667.73   268.4 1666.93     278 1666.65   286.9 1667.65
   291.11670.182   296.8 1672.44  310.741672.298   325.3 1671.58   342.1 1674.02
   346.7 1676.36   360.3 1686.44   393.2 1704.49   410.2 1706.66  435.761707.217
     442 1709.24   460.1 1718.01  506.321731.069     560 1747.31   623.1 1772.15
#Mann= 7 ,-1 , 0
       0      .1       0   20.37     .05       0   260.3    .045       0
   291.1     .05       0  310.74     .06       0  435.76      .1       0
  506.32      .1       0
#XS Ineff= 2 , 0
          151.01 1681.37  297.24         1679.61
Permanent Ineff=
       F       F
Bank Sta=260.3,291.1
XS Rating Curve= 0 ,0
Exp/Cntr(USF)=0,0
Exp/Cntr=0.5,0.3

Type RM Length L Ch R = 1 ,1172    ,25.8,25.8,25.3
XS GIS Cut Line= 4
 2422820.2879553653728.5147388592423043.38739004653943.746671485
2423150.77414874653989.1706031932423464.33333808654071.194156409
#Sta/Elev= 30
       0 1679.67     .551679.615    31.7 1672.47    47.9 1670.86     109 1671.33
   147.9 1669.15   197.9 1671.33     258 1667.04   292.4 1667.75     318 1670.69
  325.571669.057   327.2  1668.3     331  1666.1   342.4 1665.36   352.7 1666.02
   357.7 1668.54   361.4  1670.6   387.5 1670.63   404.8 1674.94   422.2 1684.29
  441.651691.501  550.261724.338  569.871731.307   600.2 1737.71   616.8 1746.03
   695.3 1772.05   711.9 1771.77     716 1772.95   728.4 1780.68   750.7 1786.61
#Mann= 8 ,-1 , 0
       0      .1       0     .55     .05       0  325.57     .06       0
   327.2    .045       0   357.7     .06       0  441.65    .055       0
  550.26      .1       0  569.87      .1       0
#XS Ineff= 2 , 0
          319.89 1673.37  361.02         1673.21
Permanent Ineff=
       F       F
Bank Sta=327.2,357.7
XS Rating Curve= 0 ,0
Exp/Cntr=0.5,0.3

Type RM Length L Ch R = 1 ,1146    ,48.2,46.6,45.2
XS GIS Cut Line= 4
2422795.69708033653754.2831470412423026.43826619653964.960461496
2423141.98026081654011.7418690762423446.87600036 654093.34550089
#Sta/Elev= 30
       0 1680.86     8.3 1679.67    30.9  1672.4   46.26 1670.37   135.7 1670.69
   161.2 1668.03   215.4 1670.54   242.5 1667.48   267.9 1666.78   329.5  1669.4
   335.7 1668.61     343 1665.62   360.2 1665.34   364.6 1665.63   369.5 1668.27
   373.2 1670.05   407.7 1669.38   420.7 1671.05     442 1680.61  465.681689.347
     486 1697.69   512.4  1706.3   524.9 1708.75  574.561723.847   624.2 1741.62
   649.1 1746.58   686.3 1760.49   702.9 1764.67   727.8 1766.22   752.7 1775.62
#Mann= 6 ,-1 , 0
       0      .1       0   46.26     .05       0   335.7    .045       0
   369.5     .06       0  465.68    .055       0  574.56      .1       0
#XS Ineff= 2 , 0
          215.33 1675.11  377.64         1674.84
Permanent Ineff=
       F       F
Bank Sta=335.7,369.5
XS Rating Curve= 0 ,0
Exp/Cntr=0.5,0.3

Type RM Length L Ch R = 1 ,1099    ,300.9,306.3,309.4
XS GIS Cut Line= 3
2422768.60765673653804.1479388172422870.63414968 653970.28978431
2423428.01023382654139.274220577
#Sta/Elev= 30
       0 1683.67     7.9  1681.2    17.3 1675.53      22 1673.88    47.2 1668.78
  112.26  1668.1   151.9 1668.77   166.4 1667.31     191 1667.35   203.4 1666.32
   236.9  1668.5   266.2 1666.03   343.1 1666.74   358.1 1668.78   365.5 1666.79
   374.8 1664.35   391.5 1664.41   399.9 1666.95  404.231668.567  468.891668.283
   483.5 1671.43   506.7 1679.08   529.1 1690.15   545.1 1695.95  625.371718.433
   671.6 1735.65   688.3 1740.96     744  1752.2   767.7 1755.11   777.4 1758.11
#Mann= 7 ,-1 , 0
       0      .1       0  112.26     .05       0   365.5    .045       0
   399.9     .05       0  404.23     .06       0  468.89    .055       0
  625.37      .1       0
#XS Ineff= 2 , 0
          235.47 1681.89  410.97         1682.26
Permanent Ineff=
       F       F
Bank Sta=365.5,399.9
XS Rating Curve= 0 ,0
Exp/Cntr(USF)=0,0
Exp/Cntr=0.3,0.1

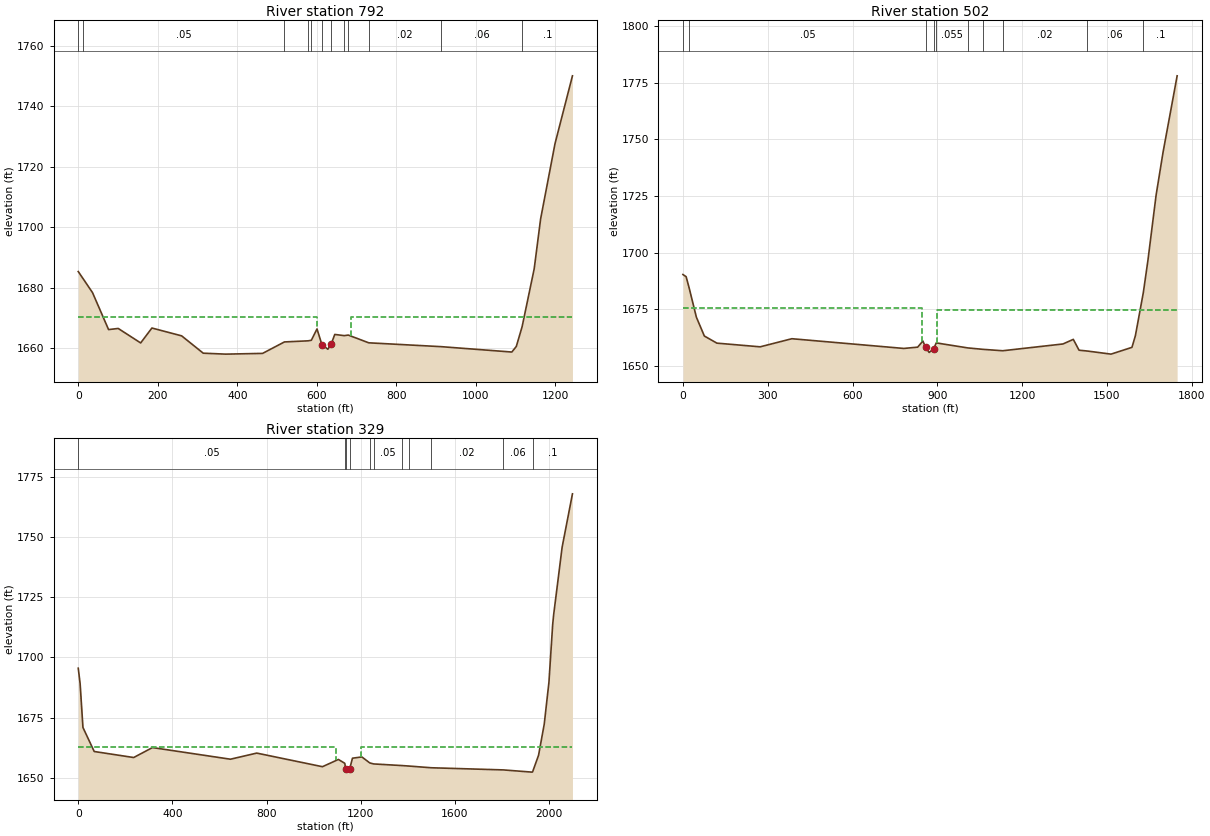
Type RM Length L Ch R = 1 ,792     ,290.8,290.3,289.8
XS GIS Cut Line= 4
2422759.90740287653811.3055914062422816.11341807654227.230103866
2423209.55552445654442.6864954562423582.38875859654403.342284818
#Sta/Elev= 30
       0  1685.4    11.7 1683.14    35.9 1678.44    76.3 1666.21   100.5 1666.59
     157  1661.8   185.3 1666.73   260.1 1664.14   314.4 1658.41   370.9  1658.1
   463.7 1658.34   518.6 1662.13   578.4  1662.5   586.4 1662.69   600.6 1666.43
   612.9 1661.25   627.9 1659.72   636.5  1661.5   645.3 1664.61   669.1 1664.21
   679.2  1664.4   730.8 1661.84   912.8 1660.57  1090.7 1658.79    1102 1660.66
  1116.6 1667.19    1147 1686.35  1163.1  1702.8  1199.3 1727.68  1243.2 1750.11
#Mann= 12 ,-1 , 0
       0      .1       0    11.7     .05       0   518.6     .05       0
   578.4     .06       0   586.4    .055       0   612.9    .045       0
   636.5    .055       0   669.1     .06       0   679.2    .035       0
   730.8     .02       0   912.8     .06       0  1116.6      .1       0
#XS Ineff= 2 , 0
          600.93 1670.41   687.3         1670.41
Permanent Ineff=
       F       F
Bank Sta=612.9,636.5
XS Rating Curve= 0 ,0
Exp/Cntr(USF)=0,0
Exp/Cntr=0.3,0.1

Type RM Length L Ch R = 1 ,502     ,175,173.6,173.8
XS GIS Cut Line= 4
2422740.96081781653819.6516707282422660.42582081654475.916038331
2423082.83185009654695.3943051522423683.90195631654583.185042273
#Sta/Elev= 30
       0  1690.3    11.3 1689.35   21.841684.459    47.6 1671.48    75.8 1663.17
   120.1 1660.03   273.3  1658.4   385.4 1661.98   781.6 1657.69   830.6 1658.26
     849 1660.98   858.5 1658.15   871.2 1655.93   887.6 1657.53  896.221660.138
 1007.451657.928 1061.021657.298 1131.27 1656.67  1344.6 1659.66  1381.3 1661.69
  1401.6 1656.91 1430.471656.552  1514.8 1655.18  1588.8 1658.17    1601 1663.33
 1629.161682.431  1645.1 1696.35  1674.2 1725.32  1698.7 1744.16  1748.7 1777.99
#Mann= 10 ,-1 , 0
       0      .1       0   21.84     .05       0   858.5    .045       0
   887.6     .06       0  896.22    .055       0 1007.45     .06       0
 1061.02    .035       0 1131.27     .02       0 1430.47     .06       0
 1629.16      .1       0
#XS Ineff= 2 , 0
          847.35 1675.32  899.91         1674.83
Permanent Ineff=
       F       F
Bank Sta=858.5,887.6
XS Rating Curve= 0 ,0
Exp/Cntr=0.3,0.1

Type RM Length L Ch R = 1 ,329     ,0,328.71,0
XS GIS Cut Line= 4
2422703.39661109653783.6337539262422519.14665151654601.328968927
2423146.62833616654915.3427765972423703.64231399654858.366840675
#Sta/Elev= 30
       0 1695.46    7.98 1689.02   19.96 1670.87   67.85  1660.9  235.49  1658.4
  315.32 1662.53  646.61  1657.7  758.37 1660.24 1037.53 1654.59 1105.31  1657.6
 1132.42    1656 1136.28 1653.71 1153.15 1653.68 1165.11 1658.12 1204.98 1658.65
 1238.42 1656.17 1254.86 1655.74  1377.3 1655.05 1406.72 1654.85 1499.75 1654.15
 1805.73 1653.26 1927.81 1652.34 1930.31 1652.41  1955.8 1659.35  1979.8 1672.21
  1999.8  1689.6  2015.8 1713.62  2019.8 1717.59 2055.79 1745.63 2099.78 1767.83
#Mann= 11 ,-1 , 0
       0     .05       0 1132.42     .06       0 1136.28    .045       0
 1153.15     .06       0 1238.42    .055       0 1254.86     .05       0
  1377.3    .035       0 1406.72     .06       0 1499.75     .02       0
 1805.73     .06       0 1930.31      .1       0
#XS Ineff= 2 , 0
         1095.85 1662.62 1202.47         1662.91
Permanent Ineff=
       F       F
Bank Sta=1136.28,1153.15
XS Rating Curve= 0 ,0
Exp/Cntr=0,0
LCMann Table=0

Chan Stop Cuts=-1
Use User Specified Reach Order=0
Composite Channel Slope=5